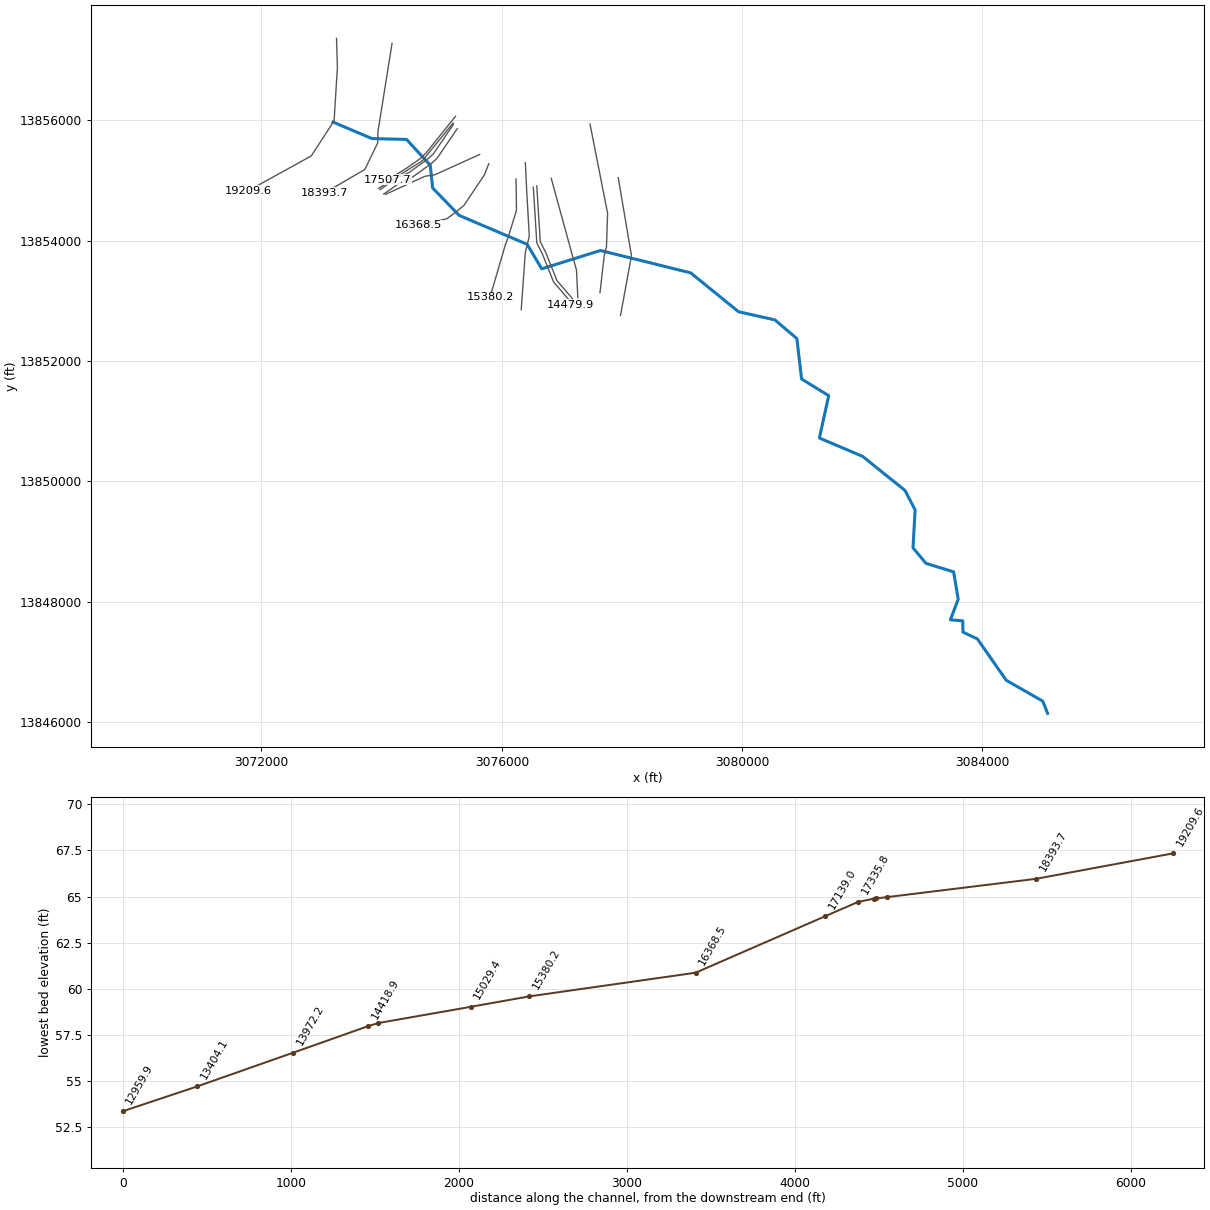
--- W140-00-00.PRJ (project) ---

Proj Title=W140-00-00
Current Plan=p03
Default Exp/Contr=.3,.1
English Units
Geom File=g01
Flow File=f01
Flow File=f03
Plan File=p01
Plan File=p03
Y Axis Title=Elevation
X Axis Title(PF)=Main Channel Distance
X Axis Title(XS)=Station
BEGIN DESCRIPTION:
Buffalo Bayou Watershed
Spring Creek
HCFCD Unit W140-00-00
Flood Hazard Model
10, 2, 1, 0.2% Event
Filename W140-00-00.prj
Prepared by:  Watershed Concepts  Date:
Reviewed by:                      Date:
STATUS FINAL
END DESCRIPTION:
DSS Export Rating Curves= 0
DSS Export Rating Curve Sorted= 0
DSS Export Volume Flow Curves= 0
DXF OffsetX= 0
DXF OffsetY= 0
DXF ScaleX= 1
DXF ScaleY= 10

--- W140-00-00.p03 (plan) ---

Plan Title=Floodway
Version=Version 3.0.1  Mar 2001
Short Identifier=Floodway0607
Geom File=g01
Flow File=f03
Subcritical Flow
K Sum by GR= 0
Std Step Tol= 0.01
Critical Tol= 0.01
Num of Std Step Trials= 20
Max Error Tol= 0.3
Flow Tol Ratio= 0.001
Split Flow NTrial= 30
Split Flow Tol= 0.02
Split Flow Ratio= 0.02
Log Output Level= 0
Friction Slope Method= 1
Unsteady Friction Slope Method= 2
Parabolic Critical Depth
Global Vel Dist= 0 , 0 , 0
Global Log Level= 0
CheckData=True
Encroach Param=-1 ,0,0, 2
Encroach River=W140-00-00
Encroach Reach=Reach - 1
Encroach Node=19209.6
       1  4981.9  5017.7
Encroach Node=18393.7
       1  4981.6  5017.5
Encroach Node=17507.7
       1 4969.31 5027.21
Encroach Node=17444.3
       1  4969.3  5027.1
Encroach Node=17433.3
       1  4969.3  5027.1
Encroach Node=17431.8
       1  4969.3  5027.1
Encroach Node=17383.8
       1  4969.3  5027.1
Encroach Node=17335.8
       1  4969.3  5027.1
Encroach Node=17139.0
       1    4983    5015
Encroach Node=16368.5
       1  4985.7  5012.7
Encroach Node=15380.2
       1  4982.1  5017.9
Encroach Node=15029.4
       1  4978.7    5022
Encroach Node=14479.9
       1  4978.7    5022
Encroach Node=14449.4
       1  4978.7    5022
Encroach Node=14418.9
       1  4978.7    5022
Encroach Node=13972.2
       1  4964.8    5021
Encroach Node=13404.1
       1  4976.6  5023.7
Encroach Node=12959.9
       1  4962.3  5046.4
Encroach Node=12859.9
       1  4962.3  5040.7
Encroach Node=12817.9
       1  4962.3  5040.7
Encroach Node=12775.9
       1  4962.3  5040.7
Encroach Node=12490.0
       1  4974.3    5052
Encroach Node=12193.4
       1  4974.3  5024.9
Encroach Node=11598.5
       1  4956.8  5043.8
Encroach Node=11492.6
       1  4956.8  5043.8
Encroach Node=11443.6
       1  4956.8  5043.8
Encroach Node=11394.6
       1  4956.8  5043.8
Encroach Node=11197.6
       1    4954    5035
Encroach Node=11108.0
       1    4950    5035
Encroach Node=11097.0
       1    4950    5035
Encroach Node=11095.7
       1    4950    5035
Encroach Node=11073.0
       1    4950    5035
Encroach Node=11050.3
       1    4950    5035
Encroach Node=11007.9
       1    4950    5033
Encroach Node=10997.4
       1    4950    5033
Encroach Node=10986.9
       1    4950    5033
Encroach Node=10363.6
       1    4965    5030
Encroach Node=9604.7
       1    4959    5025
Encroach Node=9178.3
       1    4964    5033
Encroach Node=8486.4
       1  4980.2    5044
Encroach Node=8058.8
       1  4970.2  5045.6
Encroach Node=7626.0
       1    4940    5035
Encroach Node=6629.4
       1    4968  5026.5
Encroach Node=5764.3
       1    4970    5030
Encroach Node=5522.1
       1  4979.7  5028.9
Encroach Node=5499.1
       1  4979.7  5028.9
Encroach Node=5485.3
       1  4969.1  5028.6
Encroach Node=5417.8
       1  4969.1  5028.6
Encroach Node=5350.3
       1  4969.1  5028.6
Encroach Node=5343.7
       1  4969.1    5031
Encroach Node=5314.7
       1    4960    5031
Encroach Node=5285.7
       1    4960    5031
Encroach Node=4805.3
       1  4973.4  5024.3
Encroach Node=4470.3
       1 4946.21 5021.01
Encroach Node=4332.0
       1    4965    5025
Encroach Node=4321.5
       1    4965    5025
Encroach Node=4320.7
       1    4977    5021
Encroach Node=4273.2
       1    4977    5021
Encroach Node=4225.7
       1    4977    5021
Encroach Node=3807.1
       1    4935    5075
Encroach Node=3403.8
       1    4950    5050
Encroach Node=3306.3
       1    4950    5050
Encroach Node=3208.8
       1    4950    5050
Encroach Node=2790.6
       1 4972.53 5024.63
Encroach Node=2557.7
       1    4960    5030
Encroach Node=2427.7
       1 4972.53 5024.63
Encroach Node=2416.7
       1 4972.53 5024.63
Encroach Node=2405.7
       1 4972.53 5024.63
Encroach Node=2340.9
       1    4935    5030
Encroach Node=2279.4
       1    4935    5030
Encroach Node=2217.9
       1    4935    5030
Encroach Node=1752.3
       1    4960    5040
Encroach Node=781.2
       1  4939.8  5041.5
Encroach Reach=W140-00-00_0008
Encroach Node=19209.6
       1  4981.9  5017.7
Encroach Node=18393.7
       1  4981.6  5017.5
Encroach Node=17507.7
       1 4969.31 5027.21
Encroach Node=17444.3
       1  4969.3  5027.1
Encroach Node=17433.3
       1  4969.3  5027.1
Encroach Node=17431.8
       1  4969.3  5027.1
Encroach Node=17383.8
       1  4969.3  5027.1
Encroach Node=17335.8
       1  4969.3  5027.1
Encroach Node=17139.0
       1    4983    5015
Encroach Node=16368.5
       1  4985.7  5012.7
Encroach Node=15380.2
       1  4982.1  5017.9
Encroach Node=15029.4
       1  4978.7    5022
Encroach Node=14479.9
       1  4978.7    5022
Encroach Node=14449.4
       1  4978.7    5022
Encroach Node=14418.9
       1  4978.7    5022
Encroach Node=13972.2
       1  4964.8    5021
Encroach Node=13404.1
       1  4976.6  5023.7
Encroach Node=12959.9
       1  4962.3  5046.4
Encroach Node=12859.9
       1  4962.3  5040.7
Encroach Node=12817.9
       1  4962.3  5040.7
Encroach Node=12775.9
       1  4962.3  5040.7
Encroach Node=12490.0
       1  4974.3    5052
Encroach Node=12193.4
       1  4974.3  5024.9
Encroach Node=11598.5
       1  4956.8  5043.8
Encroach Node=11492.6
       1  4956.8  5043.8
Encroach Node=11443.6
       1  4956.8  5043.8
Encroach Node=11394.6
       1  4956.8  5043.8
Encroach Node=11197.6
       1    4954    5035
Encroach Node=11108.0
       1    4950    5035
Encroach Node=11097.0
       1    4950    5035
Encroach Node=11095.7
       1    4950    5035
Encroach Node=11073.0
       1    4950    5035
Encroach Node=11050.3
       1    4950    5035
Encroach Node=11007.9
       1    4950    5033
Encroach Node=10997.4
       1    4950    5033
Encroach Node=10986.9
       1    4950    5033
Encroach Node=10363.6
       1    4965    5030
Encroach Node=9604.7
       1    4959    5025
Encroach Node=9178.3
       1    4964    5033
Encroach Node=8486.4
       1  4980.2    5044
Encroach Node=8058.8
       1  4970.2  5045.6
Encroach Node=7626.0
       1    4940    5035
Encroach Node=6629.4
       1    4968  5026.5
Encroach Node=5764.3
       1    4970    5030
Encroach Node=5522.1
       1  4979.7  5028.9
Encroach Node=5499.1
       1  4979.7  5028.9
Encroach Node=5485.3
       1  4969.1  5028.6
Encroach Node=5417.8
       1  4969.1  5028.6
Encroach Node=5350.3
       1  4969.1  5028.6
Encroach Node=5343.7
       1  4969.1    5031
Encroach Node=5314.7
       1    4960    5031
Encroach Node=5285.7
       1    4960    5031
Encroach Node=4805.3
       1  4973.4  5024.3
Encroach Node=4470.3
       1 4946.21 5021.01
Encroach Node=4332.0
       1    4965    5025
Encroach Node=4321.5
       1    4965    5025
Encroach Node=4320.7
       1    4977    5021
Encroach Node=4273.2
       1    4977    5021
Encroach Node=4225.7
       1    4977    5021
Encroach Node=3807.1
       1    4935    5075
Encroach Node=3403.8
       1    4950    5050
Encroach Node=3306.3
       1    4950    5050
Encroach Node=3208.8
       1    4950    5050
Encroach Node=2790.6
       1 4972.53 5024.63
Encroach Node=2557.7
       1    4960    5030
Encroach Node=2427.7
       1 4972.53 5024.63
Encroach Node=2416.7
       1 4972.53 5024.63
Encroach Node=2405.7
       1 4972.53 5024.63
Encroach Node=2340.9
       1    4935    5030
Encroach Node=2279.4
       1    4935    5030
Encroach Node=2217.9
       1    4935    5030
Encroach Node=1752.3
       1    4960    5040
Encroach Node=781.2
       1  4939.8  5041.5
Computation Interval=1HOUR
Output Interval=1HOUR
Run HTab= 0
Run UNet= 0
Run PostProcess= 0
UNET Theta= 1
UNET ZTol= 0.02
UNET ZSATol= 0.1
UNET MxIter= 20
UNET MaxInSteps= 20
UNET DtIC= 0
UNET DtMin= 0
UNET MaxCRTS= 20
UNET WFStab= 2
UNET SFStab= 1
UNET WFX= 1
UNET SFX= 1
UNET Convert EG Bridges=-1
UNET Use Existing IB Tables=-1
Instantaneous Interval=1HOUR
Write IC File= 0
IC Time=0
Write Velocity= 0
Write Detailed= 0

--- W140-00-00.p01 (plan) ---

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Plan Title=FEMA Effective June 2007
Program Version=3.13
Short Identifier=FEMAeff0607
Geom File=g01
Flow File=f01
Unsteady Bridges Friction Slope Method= 1
Encroach Param=-1 ,0,0, 0
UNET Theta Warmup= 1
UNET ZSATol= 0.05
UNET MaxInSteps= 0
UNET DSS MLevel= 4
UNET DZMax Abort= 100
UNET Froude Reduction=False
UNET Froude Limit= 1
UNET Froude Power= 10
Echo Input=False
Echo Output=False
Detailed Automatic Start=False, 10

--- W140-00-00.f03 (steady flow) ---

Flow Title=Floodway
Program Version=3.13
Number of Profiles= 2
Profile Names=1PCT_100yr,1PCTFloodway_100yrFW
River Rch & RM=W140-00-00,W140-00-00_0008       ,19209.6
    1760    1760
River Rch & RM=W140-00-00,W140-00-00_0008       ,15380.2
    2106    2106
River Rch & RM=W140-00-00,W140-00-00_0008       ,13404.1
    2888    2888
River Rch & RM=W140-00-00,W140-00-00_0008       ,12859.9
    3151    3151
River Rch & RM=W140-00-00,W140-00-00_0008       ,12193.4
    3394    3394
River Rch & RM=W140-00-00,W140-00-00_0008       ,11007.9
    3898    3898
River Rch & RM=W140-00-00,W140-00-00_0008      ,10363.6
    4158    4158
River Rch & RM=W140-00-00,W140-00-00_0008      ,9604.7
    4475    4475
River Rch & RM=W140-00-00,W140-00-00_0008       ,8486.4
    4942    4942
River Rch & RM=W140-00-00,W140-00-00_0008      ,7626
    5301    5301
River Rch & RM=W140-00-00,W140-00-00_0008     ,6629.4
    5717    5717
River Rch & RM=W140-00-00,W140-00-00_0008       ,3306.3
    7125    7125
River Rch & RM=W140-00-00,W140-00-00_0008       ,2790.6
    7121    7121
River Rch & RM=W140-00-00,W140-00-00_0008       ,2340.9
    7117    7117
River Rch & RM=W140-00-00,W140-00-00_0008       ,1752.3
    7113    7113
River Rch & RM=W140-00-00,W140-00-00_0008       ,781.2
    7104    7104
Boundary for River Rch & Prof#=W140-00-00,W140-00-00_0008       , 1
Up Type= 0
Dn Type= 3
Dn Slope=0.0026
Boundary for River Rch & Prof#=W140-00-00,W140-00-00_0008       , 2
Up Type= 0
Dn Type= 3
Dn Slope=0.0026
DSS Import GetInterval= 0
DSS Import GetPeak= 0
DSS Import FillOption= 0

--- W140-00-00.f01 (steady flow) ---

Flow Title=FEMA Effective June 2007
Program Version=3.13
Number of Profiles= 4
Profile Names=10PCT_10yr, 2PCT_50yr, 1PCT_100yr,0.2PCT_500yr
River Rch & RM=W140-00-00,W140-00-00_0008 ,19209.6
     994    1498    1760    2508
River Rch & RM=W140-00-00,W140-00-00_0008 ,15380.2
    1190    1793    2106    3001
River Rch & RM=W140-00-00,W140-00-00_0008 ,13404.1
    1619    2453    2888    4167
River Rch & RM=W140-00-00,W140-00-00_0008 ,12859.9
    1757    2674    3151    4551
River Rch & RM=W140-00-00,W140-00-00_0008 ,12193.4
    1885    2880    3394    4908
River Rch & RM=W140-00-00,W140-00-00_0008 ,11007.9
    2149    3305    3898    5646
River Rch & RM=W140-00-00,W140-00-00_0008 ,10363.6
    2286    3525    4158    6028
River Rch & RM=W140-00-00,W140-00-00_0008 ,9604.7
    2453    3793    4475    6492
River Rch & RM=W140-00-00,W140-00-00_0008 ,8486.4
    2698    4188    4942    7177
River Rch & RM=W140-00-00,W140-00-00_0008 ,7626
    2887    4491    5301    7703
River Rch & RM=W140-00-00,W140-00-00_0008 ,6629.4
    3106    4843    5717    8313
River Rch & RM=W140-00-00,W140-00-00_0008 ,3306.3
    3846    6033    7125   10378
River Rch & RM=W140-00-00,W140-00-00_0008 ,2790.6
    3847    6026    7121   10378
River Rch & RM=W140-00-00,W140-00-00_0008 ,2340.9
    3849    6018    7117   10378
River Rch & RM=W140-00-00,W140-00-00_0008 ,1752.3
    3850    6011    7113   10379
River Rch & RM=W140-00-00,W140-00-00_0008 ,781.2
    3853    5996    7104   10379
Boundary for River Rch & Prof#=W140-00-00,W140-00-00_0008 , 1
Up Type= 0
Dn Type= 3
Dn Slope=0.0026
Boundary for River Rch & Prof#=W140-00-00,W140-00-00_0008 , 2
Up Type= 0
Dn Type= 3
Dn Slope=0.0026
Boundary for River Rch & Prof#=W140-00-00,W140-00-00_0008 , 3
Up Type= 0
Dn Type= 3
Dn Slope=0.0026
Boundary for River Rch & Prof#=W140-00-00,W140-00-00_0008 , 4
Up Type= 0
Dn Type= 3
Dn Slope=0.0026
DSS Import GetInterval= 0
DSS Import GetPeak= 0
DSS Import FillOption= 0

--- W140-00-00.g01 (geometry) ---

Geom Title=W140-00-00 June 2007
Program Version=3.13

River Reach=W140-00-00      ,W140-00-00_0008
Reach XY= 30
      3073193.52     13855972.75      3073839.75       13855699.
        3074415.       13855685.      3074809.97     13855255.91
       3074849.5       13854878.      3075290.75       13854422.
       3076423.5       13853940.        3076665.       13853533.
      3077643.09     13853837.99       3079144.5       13853466.
      3079940.91     13852819.77      3080545.65     13852684.02
        3080912.       13852373.      3080990.48     13851700.88
      3081441.76     13851423.66      3081286.59     13850719.64
      3082005.86     13850414.73      3082711.79     13849847.41
      3082880.15     13849524.48      3082844.84      13848894.3
      3083059.92      13848635.4      3083520.87     13848493.57
      3083597.26     13848038.66      3083466.38     13847696.53
      3083672.83     13847679.53      3083675.99     13847492.53
      3083918.47     13847376.84      3084394.67     13846692.51
      3085004.31     13846343.67      3085084.88      13846140.7

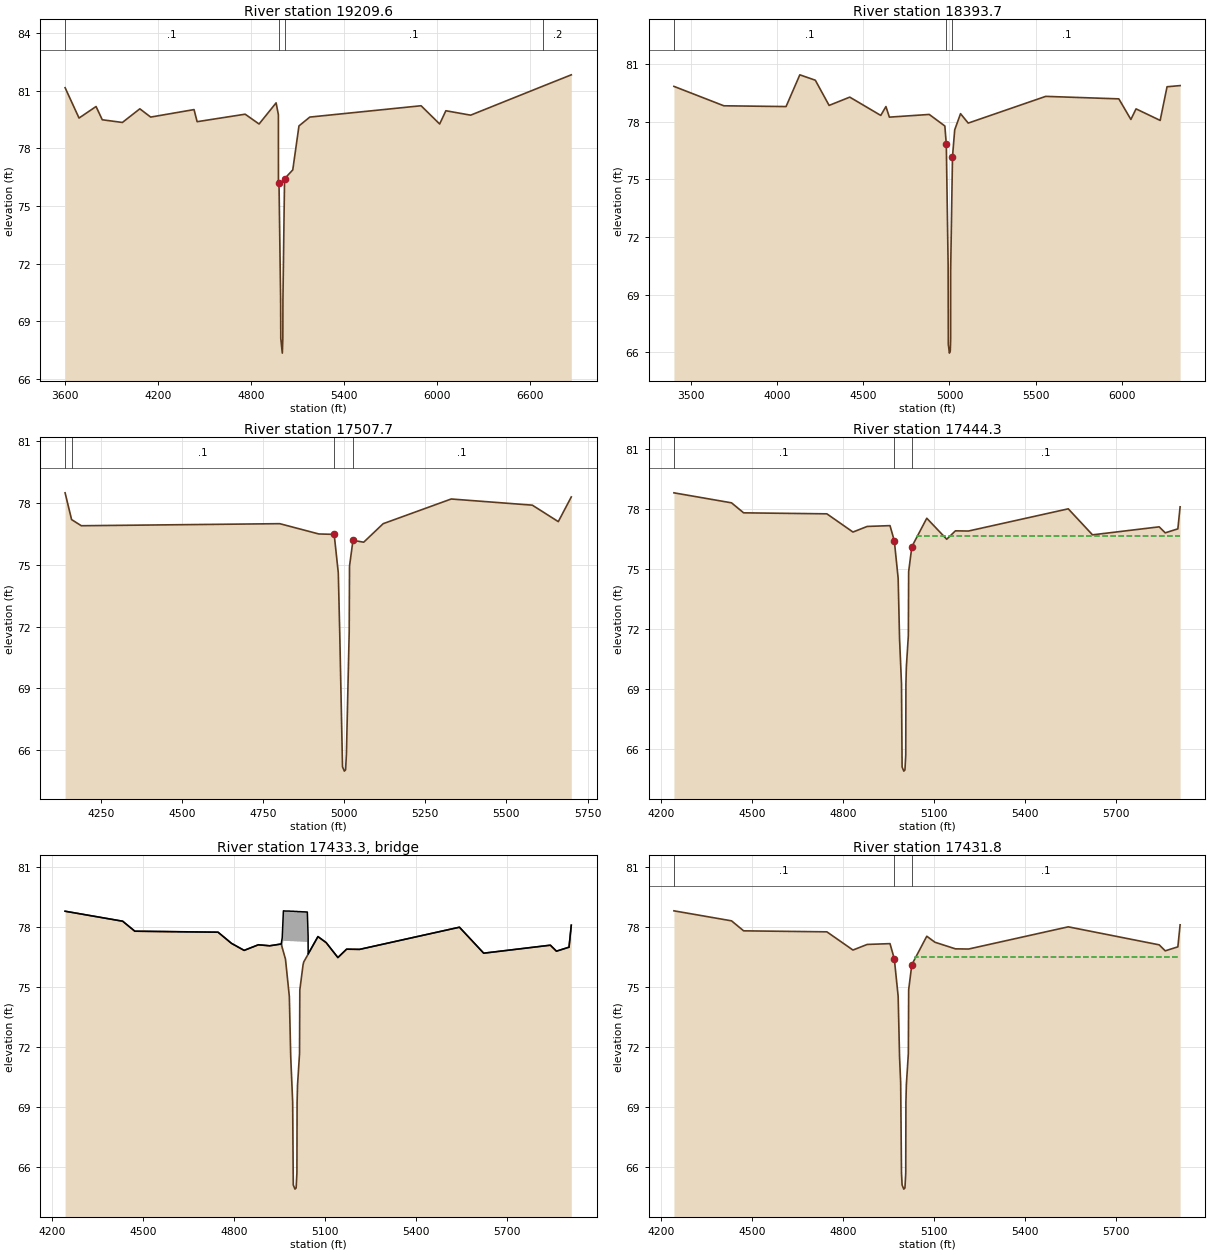
Type RM Length L Ch R = 1 ,19209.6 ,806.5,815.9,820.2
BEGIN DESCRIPTION:
Cross Section 19209.6
END DESCRIPTION:
XS GIS Cut Line= 6
      3073250.11     13857365.87      3073264.51     13856883.42
      3073209.84     13856000.29      3073172.69     13855937.67
      3072829.86     13855410.81      3071779.32     13854830.79
#Sta/Elev= 30
  3600.5   81.16  3690.5   79.58  3800.5   80.18  3840.5   79.49  3970.5   79.35
  4083.2   80.06  4153.2   79.63  4433.2   80.02  4453.2   79.39  4763.2   79.78
  4853.2   79.27  4963.2   80.37    4978   79.75  4978.3   76.25  4981.9   76.21
  4992.3   70.19  4993.4    68.1  5003.3   67.34  5006.6    68.1  5007.3   70.12
  5017.7   76.42  5070.8   76.88  5110.8   79.17  5180.8   79.63  5899.4   80.22
  6019.4   79.27  6059.4   79.96  6219.4   79.73  6689.1   81.25  6869.4   81.83
#Mann= 4 , 1 , 0
  3600.5      .1       0  4981.9    .015       0  5017.7      .1       0
  6689.1      .2       0
Bank Sta=4981.9,5017.7
Exp/Cntr=0.3,0.1

Type RM Length L Ch R = 1 ,18393.7 ,1152.7,886,551
BEGIN DESCRIPTION:
Cross Section 18393.7
END DESCRIPTION:
XS GIS Cut Line= 6
      3074173.92      13857280.5      3074107.38     13856864.73
      3073939.67     13855816.54      3073936.71     13855630.22
      3073721.44     13855184.99      3073050.89     13854794.67
#Sta/Elev= 30
  3399.9   79.83  3689.9   78.82    4051   78.78    4131   80.43    4221   80.15
    4301   78.84    4421   79.27    4601   78.32    4631   78.78    4651   78.23
  4882.5   78.37  4973.1   77.77  4981.6   76.82  4992.2   70.54  4993.3   66.41
  4999.6   65.96  5004.7   66.08  5006.7   66.68  5006.8   70.22  5017.5   76.17
  5030.4   77.57  5064.2   78.41  5108.8   77.92  5558.8   79.31  5983.4   79.18
  6053.4   78.11  6083.4   78.66  6223.4   78.06  6263.4   79.81  6339.2   79.87
#Mann= 3 , 1 , 0
  3399.9      .1       0  4981.6    .015       0  5017.5      .1       0
Bank Sta=4981.6,5017.5
Exp/Cntr=0.3,0.1

Type RM Length L Ch R = 1 ,17507.7 ,52.8,63.4,65.9
BEGIN DESCRIPTION:
Cross Section 17507.7-Interpolated
END DESCRIPTION:
XS GIS Cut Line= 6
      3075230.09     13856068.48      3074884.05     13855639.26
      3074739.74     13855459.67      3074640.32     13855363.47
      3074419.04     13855209.54      3074105.72     13855012.59
#Sta/Elev= 21
  4140.2    78.5  4160.2    77.2  4190.2    76.9  4801.6      77    4922    76.5
 4969.31   76.48 4982.01   74.61 4986.61   71.59 4995.01   65.18 5000.61   64.97
 5004.41   65.03 5007.01   65.78 5015.61   71.74 5016.61   74.94 5027.21   76.19
  5060.3    76.1  5120.3      77  5329.9    78.2  5579.9    77.9  5659.9    77.1
  5699.9    78.3
#Mann= 4 , 1 , 0
  4140.2      .2       0  4160.2      .1       0 4969.31    .015       0
 5027.21      .1       0
#XS Ineff= 2 , 0
       0                  5579.3       0   77.85
Permanent Ineff=
       F       F
Bank Sta=4969.31,5027.21
Exp/Cntr=0.5,0.3

Type RM Length L Ch R = 1 ,17444.3 ,12.5,12.5,12.5
BEGIN DESCRIPTION:
Upstream Section of Bridge/Culvert/Weir
END DESCRIPTION:
XS GIS Cut Line= 5
      3075190.77     13855956.97      3074736.62     13855401.89
      3074713.47     13855365.24      3074658.11     13855317.33
      3073950.55      13854871.6
#Sta/Elev= 30
  4242.2   78.81  4432.2   78.31  4472.2   77.81 4746.81   77.76 4832.91   76.85
 4879.81   77.13 4955.11   77.17 4969.31   76.41 4982.01   74.54 4986.61   71.52
 4993.01   69.26 4995.01   65.11 5000.61    64.9 5004.41   64.96 5007.01   65.71
 5007.61   69.24 5009.01    70.1 5015.61   71.67 5016.61   74.87 5027.21   76.12
 5076.41   77.54 5142.21   76.49 5170.91   76.91 5213.71    76.9  5543.2   78.01
  5623.2   76.71  5843.2   77.11  5863.2   76.81  5904.8   77.01  5912.2   78.11
#Mann= 3 , 1 , 0
  4242.2      .1       0 4969.31    .015       0 5027.21      .1       0
#XS Ineff= 2 , 0
       0    4952   77.16    5044       0   76.66
Permanent Ineff=
       F       F
Bank Sta=4969.31,5027.21
Exp/Cntr=0.5,0.3

Type RM Length L Ch R = 3 ,17433.3 ,,,
BEGIN DESCRIPTION:
24" PIPELINE U/S OF LONG POINT ROAD
END DESCRIPTION:
Bridge Culvert--1,0,-1,-1, 0
Deck Dist Width WeirC Skew NumUp NumDn MinLoCord MaxHiCord MaxSubmerge Is_Ogee
10,2,2.6,0, 43, 43, , , 0.95, 0, 1,1,,
  4242.2  4432.2  4472.2 4746.81 4791.31 4832.91 4879.81 4917.41 4955.11 4958.51
 4958.62 4958.71 4962.41 4969.31 4982.01 4986.61 4990.31 4993.01 4995.01 5000.61
 5004.41 5007.01 5007.61 5009.01 5015.61 5016.61 5027.21 5029.51 5041.41  5043.9
 5044.01 5044.11 5076.41 5103.41 5142.21 5170.91 5213.71  5543.2  5623.2  5843.2
  5863.2  5904.8  5912.2
    78.8    78.3    77.8   77.75   77.19   76.84   77.12   77.07   77.16   77.47
   77.51   77.54   78.82   78.81   78.81    78.8    78.8    78.8    78.8   78.79
   78.79   78.79   78.79   78.78   78.78   78.78   78.77   78.77   78.76   77.59
   77.54   76.66   77.53   77.23   76.48    76.9   76.89      78    76.7    77.1
    76.8      77    78.1
    78.8    78.3    77.8   77.75   77.19   76.84   77.12   77.07   77.16   76.98
   76.97   76.97   77.32   77.31   77.31    77.3    77.3    77.3    77.3   77.29
   77.29   77.29   77.29   77.28   77.28   77.28   77.27   77.27   77.26   76.65
   76.65   76.66   77.53   77.23   76.48    76.9   76.89      78    76.7    77.1
    76.8      77    78.1
  4242.2  4432.2  4472.2 4746.81 4791.31 4832.91 4879.81 4917.41 4955.11 4958.51
 4958.62 4958.71 4962.41 4969.31 4982.01 4986.61 4990.31 4993.01 4995.01 5000.61
 5004.41 5007.01 5007.61 5009.01 5015.61 5016.61 5027.21 5029.51 5041.41  5043.9
 5044.01 5044.11 5076.41 5103.41 5142.21 5170.91 5213.71  5543.2  5623.2  5843.2
  5863.2  5904.8  5912.2
    78.8    78.3    77.8   77.75   77.19   76.84   77.12   77.07   77.16   77.47
   77.51   77.54   78.82   78.81   78.81    78.8    78.8    78.8    78.8   78.79
   78.79   78.79   78.79   78.78   78.78   78.78   78.77   78.77   78.76   77.59
   77.54   76.66   77.53   77.23   76.48    76.9   76.89      78    76.7    77.1
    76.8      77    78.1
    78.8    78.3    77.8   77.75   77.19   76.84   77.12   77.07   77.16   76.98
   76.97   76.97   77.32   77.31   77.31    77.3    77.3    77.3    77.3   77.29
   77.29   77.29   77.29   77.28   77.28   77.28   77.27   77.27   77.26   76.65
   76.65   76.66   77.53   77.23   76.48    76.9   76.89      78    76.7    77.1
    76.8      77    78.1
BR Coef= 1 , 1 , 0 ,1.25, 0 ,,,0.8,0,2,0,
WSPro=,,,, 1 ,,,, 0 ,,,, 0 ,,,,-1 ,-1 ,-1 , 0 , 0 , 0 , 0 , 0
BR U #Sta/Elev= 43
  4242.2    78.8  4432.2    78.3  4472.2    77.8 4746.81   77.75 4791.31   77.19
 4832.91   76.84 4879.81   77.12 4917.41   77.07 4955.11   77.16 4958.51   76.98
 4958.62   76.97 4958.71   76.97 4962.41   76.77 4969.31    76.4 4982.01   74.53
 4986.61   71.51 4990.31    70.2 4993.01   69.25 4995.01    65.1 5000.61   64.89
 5004.41   64.95 5007.01    65.7 5007.61   69.23 5009.01   70.09 5015.61   71.66
 5016.61   74.86 5027.21   76.11 5029.51   76.26 5041.41   76.58  5043.9   76.65
 5044.01   76.65 5044.11   76.66 5076.41   77.53 5103.41   77.23 5142.21   76.48
 5170.91    76.9 5213.71   76.89  5543.2      78  5623.2    76.7  5843.2    77.1
  5863.2    76.8  5904.8      77  5912.2    78.1
BR U #Mann= 3
  4242.2      .1 4969.31    .015 5027.21      .1
BR U Banks=4969.31,5027.21
BR D #Sta/Elev= 43
  4242.2    78.8  4432.2    78.3  4472.2    77.8 4746.81   77.75 4791.31   77.19
 4832.91   76.84 4879.81   77.12 4917.41   77.07 4955.11   77.16 4958.51   76.98
 4958.62   76.97 4958.71   76.97 4962.41   76.77 4969.31    76.4 4982.01   74.53
 4986.61   71.51 4990.31    70.2 4993.01   69.25 4995.01    65.1 5000.61   64.89
 5004.41   64.95 5007.01    65.7 5007.61   69.23 5009.01   70.09 5015.61   71.66
 5016.61   74.86 5027.21   76.11 5029.51   76.26 5041.41   76.58  5043.9   76.65
 5044.01   76.65 5044.11   76.66 5076.41   77.53 5103.41   77.23 5142.21   76.48
 5170.91    76.9 5213.71   76.89  5543.2      78  5623.2    76.7  5843.2    77.1
  5863.2    76.8  5904.8      77  5912.2    78.1
BR D #Mann= 3
  4242.2      .1 4969.31    .015 5027.21      .1
BR D Banks=4969.31,5027.21
BC Design=,, 0 ,, 0 ,,,,,,
BC HTab HWMax=78.81

Type RM Length L Ch R = 1 ,17431.8 ,96,96,96
BEGIN DESCRIPTION:
Upstream Section of Bridge/Culvert/Weir
END DESCRIPTION:
XS GIS Cut Line= 6
      3075196.89     13855936.16      3074859.47     13855441.91
      3074766.49     13855358.23      3074458.61     13855135.36
      3074241.98     13855036.69       3073973.7     13854848.74
#Sta/Elev= 30
  4242.2    78.8  4432.2    78.3  4472.2    77.8  4746.8   77.75  4832.9   76.84
  4879.8   77.12  4955.1   77.16  4969.3    76.4    4982   74.53  4986.6   71.51
  4990.3    70.2    4993    65.7    4995    65.1  5000.6   64.89  5004.4   64.95
    5007    65.7  5007.6   69.23    5009   70.09  5015.6   71.66  5016.7   74.86
  5027.1   76.11  5076.4   77.53  5103.4   77.23  5170.9    76.9  5214.2   76.89
  5543.2      78  5843.2    77.1  5863.2    76.8  5904.8      77  5912.2    78.1
#Mann= 3 , 1 , 0
  4242.2      .1       0  4969.3    .017       0  5027.1      .1       0
#XS Ineff= 2 , 0
       0    4962   76.78  5037.3       0   76.47
Permanent Ineff=
       F       F
Bank Sta=4969.3,5027.1
Exp/Cntr=0.5,0.3

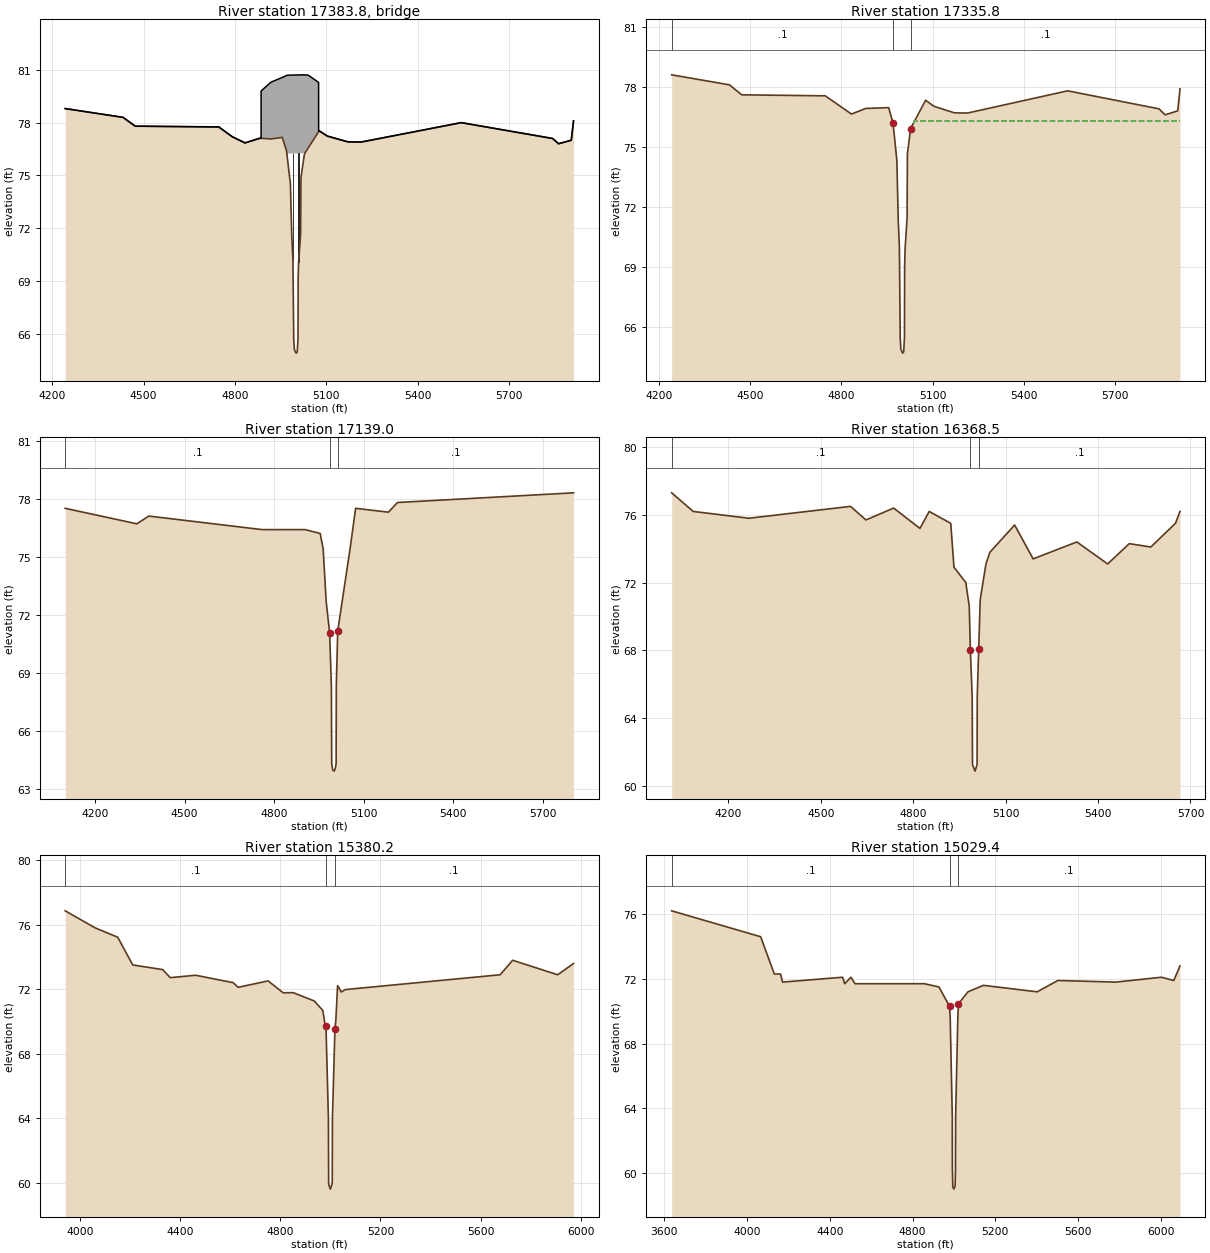
Type RM Length L Ch R = 3 ,17383.8 ,,,
BEGIN DESCRIPTION:
LONG POINT ROAD
Structure ID: W40-17
END DESCRIPTION:
Bridge Culvert--1,0,-1,-1, 0
Deck Dist Width WeirC Skew NumUp NumDn MinLoCord MaxHiCord MaxSubmerge Is_Ogee
10,76,2.6,0, 28, 28, , , 0.95, 0, 1,1,,
  4242.2  4432.2  4472.2  4746.8  4791.3  4832.9 4885.69  4885.8  4917.9  4955.1
  4969.3 4972.21  4972.3 5027.19  5027.3  5029.5  5040.6  5074.7 5074.81  5076.4
  5103.4  5170.9  5214.2  5543.2  5843.2  5863.2  5904.8  5912.2
    78.8    78.3    77.8   77.76    77.2   76.85   77.12    79.8    80.3   80.57
   80.68    80.7    80.7   80.72   80.72   80.72    80.7   80.29    77.5   77.54
   77.24   76.91    76.9      78    77.1    76.8      77    78.1
    78.8    78.3    77.8   77.75   77.19   76.84   77.11   77.11   77.07   77.16
    76.4   75.97   76.24   76.26   76.12   76.26   76.56   77.48   77.49   77.53
   77.23    76.9   76.89      78    77.1    76.8      77    78.1
  4242.2  4432.2  4472.2  4746.8  4791.3  4832.9 4885.69  4885.8  4917.9  4955.1
  4969.3 4972.21  4972.3 5027.19  5027.3  5029.5  5040.6  5074.7 5074.81  5076.4
  5103.4  5170.9  5214.2  5543.2  5843.2  5863.2  5904.8  5912.2
    78.8    78.3    77.8   77.76    77.2   76.85   77.12    79.8    80.3   80.57
   80.68    80.7    80.7   80.72   80.72   80.72    80.7   80.29    77.5   77.54
   77.24   76.91    76.9      78    77.1    76.8      77    78.1
   78.66   78.16   77.66   77.61   77.05    76.7   76.97   76.97   76.93   77.02
   76.26   75.83    76.1   76.12   75.98   76.12   76.42   77.34   77.35   77.39
   77.09   76.76   76.75   77.86   76.96   76.66   76.86   77.96
Pier Skew, UpSta & Num, DnSta & Num=  ,4990.3, 2 ,4990.3, 2 , 0 , 0 , 0 ,,
     1.3     1.3
   68.12   77.25
     1.3     1.3
   67.98   77.11
Pier Skew, UpSta & Num, DnSta & Num=  ,5009, 2 ,5009, 2 , 0 , 0 , 0 ,,
     1.3     1.3
   68.69   77.25
     1.3     1.3
   68.55   77.11
Abutment Skew #Up #Dn= , 2 , 2
  4972.1  4992.9
   76.24   65.87
  4972.1  4992.9
    76.1   65.73
Abutment Skew #Up #Dn= , 2 , 2
  5007.4 5027.39
   68.05   76.26
  5007.4 5027.39
   67.91   76.12
BR Coef= 1 , 1 , 0 ,1.25, 0 ,,,0.8,0,2,0,
WSPro=,,,, 1 ,,,, 0 ,,,, 0 ,,,,-1 ,-1 ,-1 , 0 , 0 , 0 , 0 , 0
BR U #Sta/Elev= 61
  4242.2    78.8  4432.2    78.3  4472.2    77.8  4734.3   77.75  4746.8   77.75
  4764.8   77.52  4791.3   77.19  4796.2   77.15    4832   76.85  4832.9   76.84
  4866.5   77.04  4879.8   77.12 4885.69   77.11  4885.8   77.11 4885.91   77.11
  4917.4   77.07  4917.9   77.07  4955.1   77.16  4969.3    76.4 4972.21   75.97
  4972.3   75.96  4972.4   75.94    4982   74.53  4986.6   71.51  4990.3    70.2
  4992.9   65.87    4993    65.7    4995    65.1  5000.6   64.89  5004.4   64.95
    5007    65.7  5007.4   68.05  5007.6   69.23    5009   70.09  5015.6   71.66
  5016.7   74.86  5027.1   76.11 5027.19   76.12  5027.3   76.12  5027.5   76.14
  5029.5   76.26  5037.3   76.47  5040.6   76.56 5074.59   77.48  5074.7   77.48
 5074.81   77.49  5076.4   77.53  5103.4   77.23  5105.4   77.22  5140.4   77.05
  5169.6   76.91  5170.9    76.9  5213.7   76.89  5214.2   76.89  5380.5   77.45
  5419.9   77.58  5543.2      78  5843.2    77.1  5863.2    76.8  5904.8      77
  5912.2    78.1
BR U #Mann= 3
  4242.2      .1  4969.3    .017  5027.1      .1
BR U Banks=4969.3,5027.1
BR D #Sta/Elev= 61
  4242.2   78.66  4432.2   78.16  4472.2   77.66  4734.3   77.61  4746.8   77.61
  4764.8   77.38  4791.3   77.05  4796.2   77.01    4832   76.71  4832.9    76.7
  4866.5    76.9  4879.8   76.98 4885.69   76.97  4885.8   76.97 4885.91   76.97
  4917.4   76.93  4917.9   76.93  4955.1   77.02  4969.3   76.26 4972.21   75.83
  4972.3   75.82  4972.4    75.8    4982   74.39  4986.6   71.37  4990.3   70.06
  4992.9   65.73    4993   65.56    4995   64.96  5000.6   64.75  5004.4   64.81
    5007   65.56  5007.4   67.91  5007.6   69.09    5009   69.95  5015.6   71.52
  5016.7   74.72  5027.1   75.97 5027.19   75.98  5027.3   75.98  5027.5      76
  5029.5   76.12  5037.3   76.33  5040.6   76.42 5074.59   77.34  5074.7   77.34
 5074.81   77.35  5076.4   77.39  5103.4   77.09  5105.4   77.08  5140.4   76.91
  5169.6   76.77  5170.9   76.76  5213.7   76.75  5214.2   76.75  5380.5   77.31
  5419.9   77.44  5543.2   77.86  5843.2   76.96  5863.2   76.66  5904.8   76.86
  5912.2   77.96
BR D #Mann= 3
  4242.2      .1  4969.3    .017  5027.1      .1
BR D Banks=4969.3,5027.1
BC Design=,, 0 ,, 0 ,,,,,,
BC HTab HWMax=78.8

Type RM Length L Ch R = 1 ,17335.8 ,196.8,196.8,196.8
BEGIN DESCRIPTION:
Downstream Section of Bridge/Culvert/Weir
END DESCRIPTION:
XS GIS Cut Line= 6
       3075259.5     13855863.39      3074922.07     13855369.13
      3074829.09     13855285.45      3074521.21     13855062.58
      3074304.58     13854963.91      3074036.31     13854775.96
#Sta/Elev= 30
  4242.2   78.62  4432.2   78.12  4472.2   77.62  4746.8   77.57  4832.9   76.66
  4879.8   76.94  4955.1   76.98  4969.3   76.22    4982   74.35  4986.6   71.33
  4990.3   70.02    4993   65.52    4995   64.92  5000.6   64.71  5004.4   64.77
    5007   65.52  5007.6   69.05    5009   69.91  5015.6   71.48  5016.7   74.68
  5027.1   75.93  5076.4   77.35  5103.4   77.05  5170.9   76.72  5214.2   76.71
  5543.2   77.82  5843.2   76.92  5863.2   76.62  5904.8   76.82  5912.2   77.92
#Mann= 3 , 1 , 0
  4242.2      .1       0  4969.3    .017       0  5027.1      .1       0
#XS Ineff= 2 , 0
       0    4962   76.61  5037.3       0   76.29
Permanent Ineff=
       F       F
Bank Sta=4969.3,5027.1
Exp/Cntr=0.5,0.3

Type RM Length L Ch R = 1 ,17139.0 ,609.4,770.5,825.6
BEGIN DESCRIPTION:
Cross Section 17139.0-Interpolated
END DESCRIPTION:
XS GIS Cut Line= 4
      3075631.63     13855434.32      3074887.25     13855097.29
      3074720.49     13855071.64      3074068.86      13854772.4
#Sta/Elev= 22
  4099.8    77.5  4339.8    76.7  4379.8    77.1  4759.8    76.4    4904    76.4
    4954    76.2    4964    75.4    4974    72.7  4985.7   71.06  4991.5   68.32
  4992.6   64.31  4996.2   63.98  5000.9   63.93  5005.1   64.09  5007.4   64.32
    5008   68.35  5012.7   71.16    5054    75.4  5072.7    77.5  5182.7    77.3
  5212.7    77.8  5802.7    78.3
#Mann= 3 , 1 , 0
  4099.8      .1       0  4985.7    .015       0  5012.7      .1       0
Bank Sta=4985.7,5012.7
Exp/Cntr=0.3,0.1

Type RM Length L Ch R = 1 ,16368.5 ,864.7,988.3,1407.9
BEGIN DESCRIPTION:
Cross Section 16368.5
END DESCRIPTION:
XS GIS Cut Line= 6
      3075784.05     13855280.98      3075710.45     13855094.34
      3075373.48      13854591.5      3075214.82     13854458.34
      3075082.35     13854365.12      3074620.46     13854255.73
#Sta/Elev= 30
  4016.1    77.3  4086.1    76.2  4266.7    75.8  4596.7    76.5  4646.7    75.7
  4736.7    76.4    4822    75.2    4852    76.2    4922    75.5  4932.4   72.91
  4970.7   72.01    4982   70.61  4985.7      68  4991.5   65.26  4992.6   61.25
  5000.9   60.87  5007.4   61.26    5008   65.29  5012.7    68.1  5017.6   70.99
  5036.1   73.09    5049   73.79  5129.4    75.4  5189.4    73.4  5331.4    74.4
  5431.4    73.1  5501.4    74.3  5571.4    74.1  5651.4    75.5  5666.1    76.2
#Mann= 3 , 1 , 0
  4016.1      .1       0  4985.7    .015       0  5012.7      .1       0
Bank Sta=4985.7,5012.7
Exp/Cntr=0.3,0.1

Type RM Length L Ch R = 1 ,15380.2 ,341.1,350.8,403.4
BEGIN DESCRIPTION:
Cross Section 15380.2
END DESCRIPTION:
XS GIS Cut Line= 5
      3076237.43     13855027.92      3076245.21      13854506.6
      3076107.76     13854060.93       3076058.7     13853928.46
      3075804.56     13853061.48
#Sta/Elev= 30
  3939.4   76.87  4059.4   75.81  4149.4   75.23  4209.4   73.51  4329.4   73.22
  4359.4   72.72  4460.8   72.87  4610.8   72.41  4630.8   72.12  4750.8   72.52
  4810.8   71.78  4850.8   71.79  4935.7   71.27  4969.5   70.68  4980.1   69.64
  4982.1    69.7  4991.8   63.99  4992.8   59.88  4999.7   59.59  5007.1   59.96
  5007.9      64  5017.9   69.52  5021.6   70.11  5028.5   72.23  5043.3   71.83
  5059.1   71.98  5678.5    72.9  5728.5    73.8  5908.5    72.9  5971.9    73.6
#Mann= 3 , 1 , 0
  3939.4      .1       0  4982.1    .017       0  5017.9      .1       0
Bank Sta=4982.1,5017.9
Exp/Cntr=0.3,0.1

Type RM Length L Ch R = 1 ,15029.4 ,429.6,549.5,507.4
BEGIN DESCRIPTION:
Cross Section 15029.4-Interpolated
END DESCRIPTION:
XS GIS Cut Line= 5
       3076393.4     13855296.89      3076414.02     13854851.53
      3076458.26     13854077.27       3076391.9     13853800.75
      3076323.99     13852853.12
#Sta/Elev= 30
  3636.4    76.2  4066.4    74.6  4132.3    72.3  4162.3    72.3  4172.3    71.8
  4462.3    72.1  4472.3    71.7  4502.3    72.1  4522.3    71.7  4857.8    71.7
  4927.8    71.5  4978.7   70.31  4981.9   69.67  4992.1    63.5  4992.5   60.27
  4994.4   59.19  4999.7   59.02  5005.8   59.22  5007.5   60.12  5008.3   63.53
  5018.7   69.53    5022   70.46  5067.8    71.2  5142.2    71.6  5402.2    71.2
  5502.2    71.9  5782.2    71.8  6002.2    72.1  6062.2    71.9  6092.2    72.8
#Mann= 3 , 1 , 0
  3636.4      .1       0  4978.7    .017       0    5022      .1       0
Bank Sta=4978.7,5022
Exp/Cntr=0.5,0.3

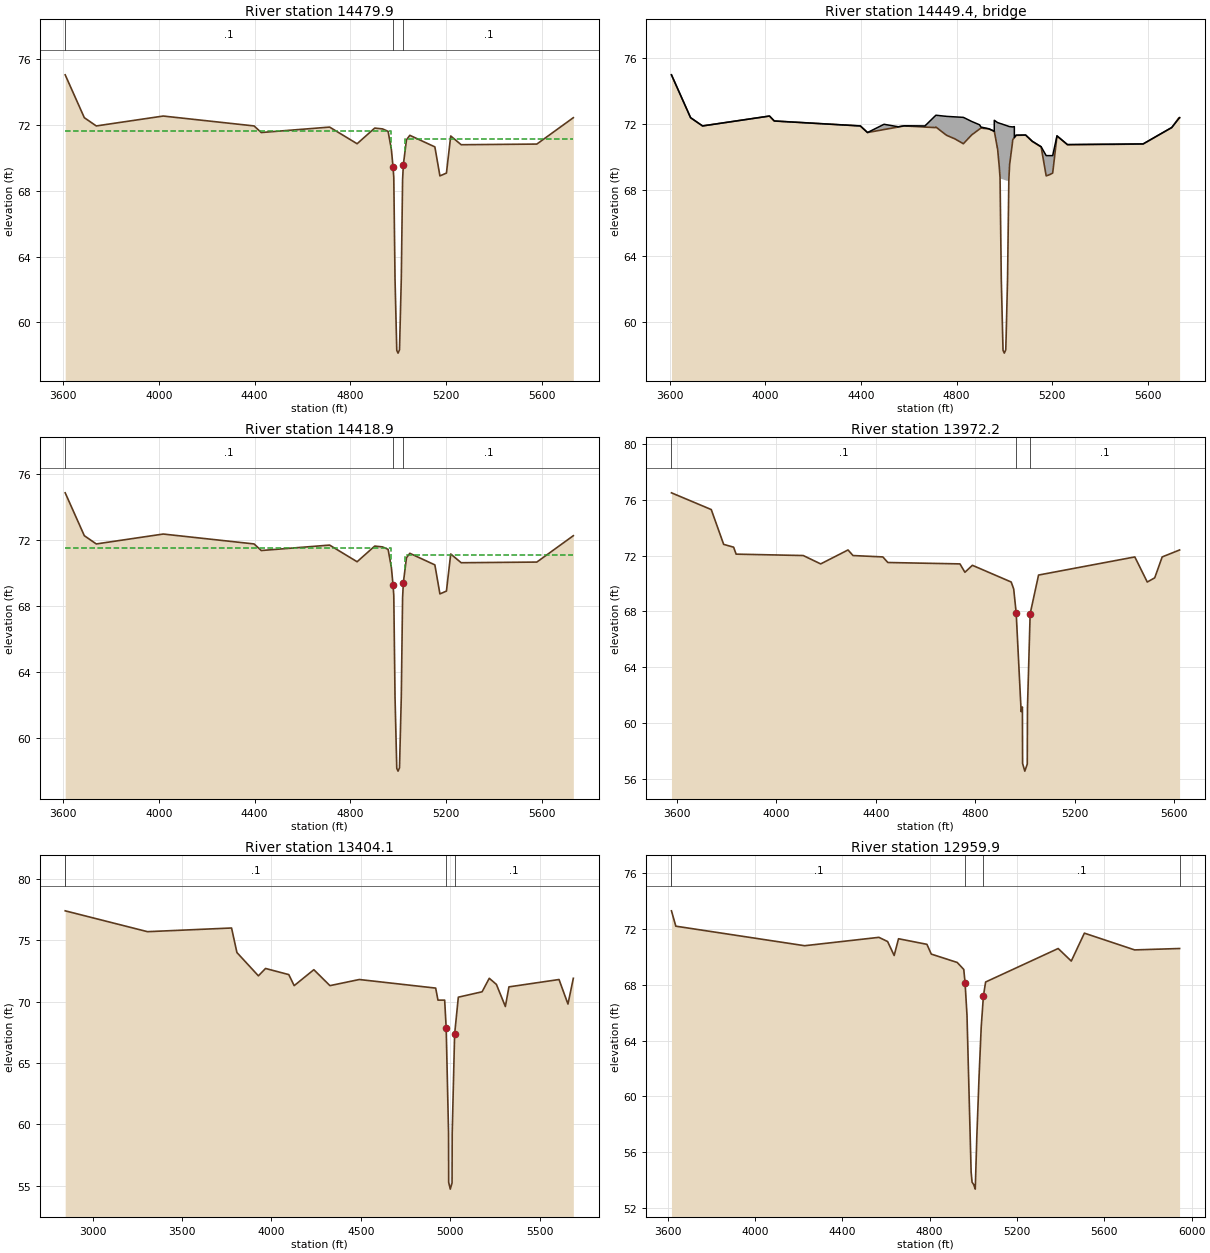
Type RM Length L Ch R = 1 ,14479.9 ,61,61,61
BEGIN DESCRIPTION:
Upstream Section of Bridge/Culvert/Weir
END DESCRIPTION:
XS GIS Cut Line= 6
      3076525.35     13854891.08       3076583.4     13853963.59
      3076677.21     13853778.34      3076861.96     13853316.47
      3077148.83     13852982.24      3077150.65     13852932.51
#Sta/Elev= 30
  3607.5   75.02  3687.5   72.42  3737.5   71.92  4017.5   72.52  4397.5   71.92
  4427.5   71.52  4713.5   71.85  4828.5   70.84  4902.2   71.79  4934.8   71.74
  4958.1   71.59  4971.9   70.49  4978.7   69.43  4981.9   68.79  4987.1   62.62
  4994.4   58.31  4999.7   58.14  5005.8   58.34  5013.3   62.65  5018.7   68.65
    5022   69.58    5035   71.08    5049   71.35  5153.7   70.65  5174.9   68.89
  5202.1   69.06    5220   71.31  5263.8   70.78  5580.3   70.82  5732.9   72.42
#Mann= 3 , 1 , 0
  3607.5      .1       0  4978.7    .015       0    5022      .1       0
#XS Ineff= 2 , 0
       0  4971.8    71.6  5028.5       0    71.1
Permanent Ineff=
       F       F
Bank Sta=4978.7,5022
Exp/Cntr=0.5,0.3

Type RM Length L Ch R = 3 ,14449.4 ,,,
BEGIN DESCRIPTION:
BRACHER ROAD
Structure ID: W40-16
END DESCRIPTION:
Bridge Culvert--1,0,-1,-1, 0
Deck Dist Width WeirC Skew NumUp NumDn MinLoCord MaxHiCord MaxSubmerge Is_Ogee
10,41,2.6,0, 42, 42, , , 0.95, 0, 1,1,,
  3607.5  3687.5  3737.5  4017.5  4037.5  4397.5  4427.5  4496.5  4556.5    4581
  4667.7  4713.5  4758.5  4828.5  4863.6  4896.2  4902.2  4934.8 4957.69  4957.8
  4958.1  4971.9  4978.7  4981.9  4987.1  5013.3  5018.7    5022    5035  5041.7
 5041.81    5049    5089  5116.8  5153.7  5174.9  5202.1    5220  5263.8  5580.3
  5700.3  5732.9
      75    72.4    71.9    72.5    72.2    71.9    71.5      72   71.85   71.91
    71.9   72.55   72.48   72.42   72.17   71.97   71.83   71.73   71.58   72.24
   72.24    72.1   72.07   72.05   72.03    71.9   71.87   71.86   71.84   71.86
    71.2   71.34   71.35   70.97   70.64    70.1    70.1    71.3   70.77   70.81
   71.81    72.4
      75    72.4    71.9    72.5    72.2    71.9    71.5   71.68   71.84    71.9
   71.83   71.83   71.33   70.82   71.36   71.71   71.77   71.72   71.57   71.57
   71.57   70.47   69.41   68.77   68.69   68.56   68.63   69.56   71.06   71.19
   71.19   71.33   71.34   70.96   70.63   68.87   69.04   71.29   70.76    70.8
    71.8    72.4
  3607.5  3687.5  3737.5  4017.5  4037.5  4397.5  4427.5  4496.5  4556.5    4581
  4667.7  4713.5  4758.5  4828.5  4863.6  4896.2  4902.2  4934.8 4957.69  4957.8
  4958.1  4971.9  4978.7  4981.9  4987.1  5013.3  5018.7    5022    5035  5041.7
 5041.81    5049    5089  5116.8  5153.7  5174.9  5202.1    5220  5263.8  5580.3
  5700.3  5732.9
      75    72.4    71.9    72.5    72.2    71.9    71.5      72   71.85   71.91
    71.9   72.55   72.48   72.42   72.17   71.97   71.83   71.73   71.58   72.24
   72.24    72.1   72.07   72.05   72.03    71.9   71.87   71.86   71.84   71.86
    71.2   71.34   71.35   70.97   70.64    70.1    70.1    71.3   70.77   70.81
   71.81    72.4
   74.88   72.28   71.78   72.38   72.08   71.78   71.38   71.56   71.72   71.78
   71.71   71.71   71.21    70.7   71.24   71.59   71.65    71.6   71.45   71.45
   71.45   70.35   69.29   68.65   68.57   68.44   68.51   69.44   70.94   71.07
   71.07   71.21   71.22   70.84   70.51   68.75   68.92   71.17   70.64   70.68
   71.68   72.28
Abutment Skew #Up #Dn= , 2 , 2
  4969.6  4992.1
   70.64   59.61
  4969.6  4992.1
   70.52   59.49
Abutment Skew #Up #Dn= , 2 , 2
  5008.3 5029.79
   59.69   70.41
  5008.3 5029.79
   59.57   70.29
BR Coef= 1 , 1 , 0 ,1.25, 0 ,,,0.8,0,2,0,
WSPro=,,,, 1 ,,,, 0 ,,,, 0 ,,,,-1 ,-1 ,-1 , 0 , 0 , 0 , 0 , 0
BR U #Sta/Elev= 83
  3607.5      75  3687.5    72.4  3737.5    71.9  4017.5    72.5  4037.5    72.2
  4397.5    71.9  4427.5    71.5  4496.5   71.68  4546.5   71.81  4556.5   71.84
    4581    71.9  4647.7   71.85  4667.7   71.83    4711    71.8  4713.5   71.83
  4714.8   71.82  4745.6   71.47  4758.5   71.33  4790.5   71.13  4791.2   71.13
  4821.3   70.88  4828.5   70.82  4863.6   71.36  4864.7   71.37  4896.2   71.71
  4902.2   71.77  4934.8   71.72  4940.2   71.69 4957.69   71.57  4957.8   71.57
 4957.91   71.57  4958.1   71.57  4969.6   70.65 4969.71   70.64  4969.8   70.64
  4971.9   70.47  4978.7   69.41  4981.9   68.77  4987.1    62.6  4992.1   59.61
  4992.5   59.37  4994.4   58.29  4999.7   58.12  5005.8   58.32  5007.5   59.22
  5008.3   59.69  5013.3   62.63  5018.7   68.63    5022   69.56 5029.59   70.41
  5029.7   70.42  5029.8   70.43  5033.3   70.82    5035   71.06 5041.59   71.19
  5041.7   71.19 5041.81   71.19    5049   71.33  5049.4   71.33    5079   71.34
    5089   71.34  5116.8   70.96  5120.3   70.93  5146.5   70.69  5153.7   70.63
  5174.9   68.87  5188.7   68.94  5202.1   69.04    5220   71.29  5222.6   71.26
  5263.8   70.76  5412.6   70.78  5452.6   70.78  5502.6   70.79  5552.6    70.8
  5562.6    70.8  5580.3    70.8    5628    71.2    5698   71.78  5700.3    71.8
  5701.2   71.82  5730.3    72.4  5732.9    72.4
BR U #Mann= 3
  3607.5      .1  4978.7    .015    5022      .1
BR U Banks=4978.7,5022
BR D #Sta/Elev= 83
  3607.5   74.88  3687.5   72.28  3737.5   71.78  4017.5   72.38  4037.5   72.08
  4397.5   71.78  4427.5   71.38  4496.5   71.56  4546.5   71.69  4556.5   71.72
    4581   71.78  4647.7   71.73  4667.7   71.71    4711   71.68  4713.5   71.71
  4714.8    71.7  4745.6   71.35  4758.5   71.21  4790.5   71.01  4791.2   71.01
  4821.3   70.76  4828.5    70.7  4863.6   71.24  4864.7   71.25  4896.2   71.59
  4902.2   71.65  4934.8    71.6  4940.2   71.57 4957.69   71.45  4957.8   71.45
 4957.91   71.45  4958.1   71.45  4969.6   70.53 4969.71   70.52  4969.8   70.52
  4971.9   70.35  4978.7   69.29  4981.9   68.65  4987.1   62.48  4992.1   59.49
  4992.5   59.25  4994.4   58.17  4999.7      58  5005.8    58.2  5007.5    59.1
  5008.3   59.57  5013.3   62.51  5018.7   68.51    5022   69.44 5029.59   70.29
  5029.7    70.3  5029.8   70.31  5033.3    70.7    5035   70.94 5041.59   71.07
  5041.7   71.07 5041.81   71.07    5049   71.21  5049.4   71.21    5079   71.22
    5089   71.22  5116.8   70.84  5120.3   70.81  5146.5   70.57  5153.7   70.51
  5174.9   68.75  5188.7   68.82  5202.1   68.92    5220   71.17  5222.6   71.14
  5263.8   70.64  5412.6   70.66  5452.6   70.66  5502.6   70.67  5552.6   70.68
  5562.6   70.68  5580.3   70.68    5628   71.08    5698   71.66  5700.3   71.68
  5701.2    71.7  5730.3   72.28  5732.9   72.28
BR D #Mann= 3
  3607.5      .1  4978.7    .015    5022      .1
BR D Banks=4978.7,5022
BC Design=,, 0 ,, 0 ,,,,,,
BC HTab HWMax=75.02

Type RM Length L Ch R = 1 ,14418.9 ,446.7,446.7,446.7
BEGIN DESCRIPTION:
Downstream Section of Bridge/Culvert/Weir
END DESCRIPTION:
XS GIS Cut Line= 6
      3076582.88     13854911.38      3076640.92     13853983.89
      3076734.73     13853798.64      3076919.48     13853336.77
      3077206.35     13853002.54      3077208.17     13852952.81
#Sta/Elev= 30
  3607.5   74.85  3687.5   72.25  3737.5   71.75  4017.5   72.35  4397.5   71.75
  4427.5   71.35  4713.5   71.68  4828.5   70.67  4902.2   71.62  4934.8   71.57
  4958.1   71.42  4971.9   70.32  4978.7   69.26  4981.9   68.62  4987.1   62.45
  4994.4   58.14  4999.7   57.97  5005.8   58.17  5013.3   62.48  5018.7   68.48
    5022   69.41    5035   70.91    5049   71.18  5153.7   70.48  5174.9   68.72
  5202.1   68.89    5220   71.14  5263.8   70.61  5580.3   70.65  5732.9   72.25
#Mann= 3 , 1 , 0
  3607.5      .1       0  4978.7    .015       0    5022      .1       0
#XS Ineff= 2 , 0
       0  4971.8    71.5  5028.5       0    71.1
Permanent Ineff=
       F       F
Bank Sta=4978.7,5022
Exp/Cntr=0.5,0.3

Type RM Length L Ch R = 1 ,13972.2 ,671.8,568.1,376.9
BEGIN DESCRIPTION:
Cross Section 13972.2-INTERPOLATED
END DESCRIPTION:
XS GIS Cut Line= 5
      3076823.26     13855039.64      3076823.27     13855039.57
      3077166.16     13853789.69      3077243.58     13853513.17
      3077266.02      13853053.8
#Sta/Elev= 30
  3578.7    76.5  3738.7    75.3  3788.7    72.8  3828.7    72.6  3838.7    72.1
  4108.7      72  4178.7    71.4  4288.7    72.4  4308.7      72  4428.7    71.9
  4448.7    71.5  4738.7    71.4  4758.7    70.8  4788.7    71.3  4944.8    70.1
  4954.8    69.6  4964.8    67.9  4984.8    60.8  4989.8   61.13  4990.6   57.08
  4999.5   56.53  5009.4   57.04  5010.2   61.05    5021   67.82  5054.8    70.6
  5441.9    71.9  5491.9    70.1  5521.9    70.4  5551.9    71.9  5621.9    72.4
#Mann= 3 , 1 , 0
  3578.7      .1       0  4964.8    .015       0    5021      .1       0
Bank Sta=4964.8,5021
Exp/Cntr=0.3,0.1

Type RM Length L Ch R = 1 ,13404.1 ,381.9,444.2,407.1
BEGIN DESCRIPTION:
Cross Section 13404.1
END DESCRIPTION:
XS GIS Cut Line= 5
      3077468.64       13855941.      3077761.81     13854455.52
      3077742.69     13853898.98      3077705.74     13853754.02
      3077635.14     13853138.04
#Sta/Elev= 30
  2846.8    77.4  3306.8    75.7  3776.8      76  3806.8      74  3926.8    72.1
  3966.8    72.7  4096.8    72.2  4126.8    71.3  4236.8    72.6  4326.8    71.3
  4490.9    71.8  4917.8    71.1  4930.7   70.12  4968.1   70.12  4976.6   67.86
  4989.8   59.31  4990.6   55.26  4999.5   54.71  5009.4   55.22  5010.2   59.23
  5023.7   67.33  5044.5   70.36  5177.4    70.8  5217.4    71.9  5257.4    71.4
  5307.4    69.6  5327.4    71.2  5607.4    71.8  5657.4    69.8  5687.4    71.9
#Mann= 4 , 1 , 0
  2846.8      .2       0  2846.8      .1       0  4976.6    .017       0
  5023.7      .1       0
Bank Sta=4976.6,5023.7
Exp/Cntr=0.3,0.1

Type RM Length L Ch R = 1 ,12959.9 ,67.4,100,155.6
BEGIN DESCRIPTION:
Cross Section 12959.9-Interpolated
END DESCRIPTION:
XS GIS Cut Line= 4
      3077938.73     13855048.39      3078157.95     13853758.11
       3078132.9     13853607.78      3077976.31     13852755.95
#Sta/Elev= 27
  3617.6    73.3  3637.6    72.2  4227.6    70.8  4567.6    71.4  4607.6    71.1
  4637.6    70.1  4657.6    71.3  4787.6    70.9  4807.6    70.2  4926.4    69.6
  4956.4    69.1  4962.3   68.16  4971.2   65.81  4990.1   54.59  4994.4   53.86
  5002.1   53.68    5009   53.36  5016.4    57.2  5026.4    61.4  5036.4      65
  5046.4    67.2  5056.4    68.2  5388.8    70.6  5448.8    69.7  5508.8    71.7
  5738.8    70.5  5944.9    70.6
#Mann= 5 , 1 , 0
  3617.6      .2       0  3617.6      .1       0  4962.3    .017       0
  5046.4      .1       0  5944.9      .2       0
Bank Sta=4962.3,5046.4
Exp/Cntr=0.5,0.3