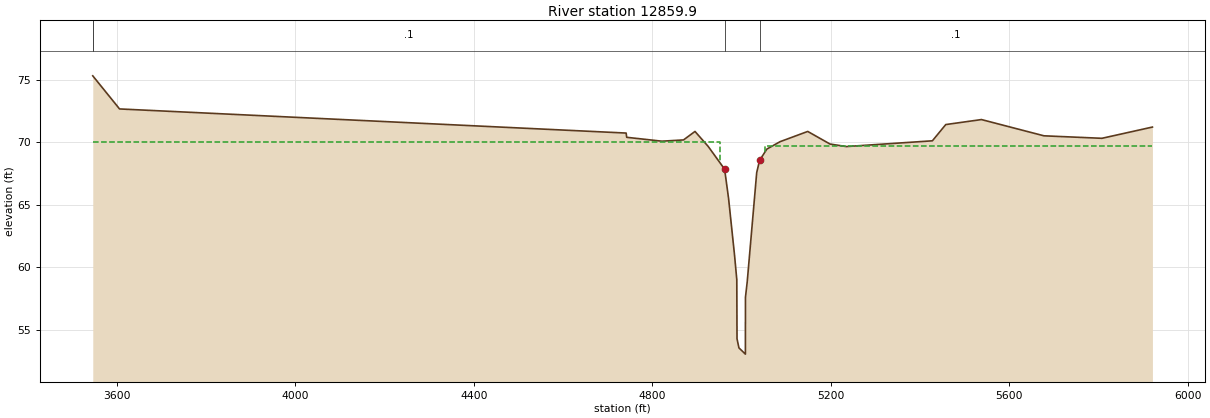
HEC-RAS study W140-00-00.PRJ: W140-00-00

--- W140-00-00.g01 (geometry) --- (continued)

Type RM Length L Ch R = 1 ,12859.9 ,84,84,84
BEGIN DESCRIPTION:
Upstream Section of Bridge/Culvert/Weir
END DESCRIPTION:
XS GIS Cut Line= 6
       3078018.1     13855088.25      3078188.81     13853885.72
      3078240.67     13853677.29      3078245.22      13853615.9
       3078227.6      13853548.5      3078251.74     13852735.12
#Sta/Elev= 30
  3546.1   75.33  3606.1   72.68  4741.6   70.75  4742.8   70.41  4821.6    70.1
  4870.2    70.2  4895.9   70.88  4925.5   69.68  4962.3   67.86  4971.2   65.51
  4984.4   61.03  4989.6   59.02  4990.1   54.29  4994.4   53.56  5008.9   53.06
    5009    57.6    5013   58.86  5034.2   67.58  5040.7   68.57  5057.1   69.47
  5086.6   70.06  5148.6   70.88  5198.6   69.87  5235.2   69.67    5428   70.13
    5458   71.43    5538   71.83    5678   70.53    5808   70.33  5921.2   71.23
#Mann= 4 , 1 , 0
  3546.1      .2       0  3546.1      .1       0  4962.3    .025       0
  5040.7      .1       0
#XS Ineff= 2 , 0
       0    4953   70.05  5053.2       0    69.7
Permanent Ineff=
       F       F
Bank Sta=4962.3,5040.7
Exp/Cntr=0.5,0.3