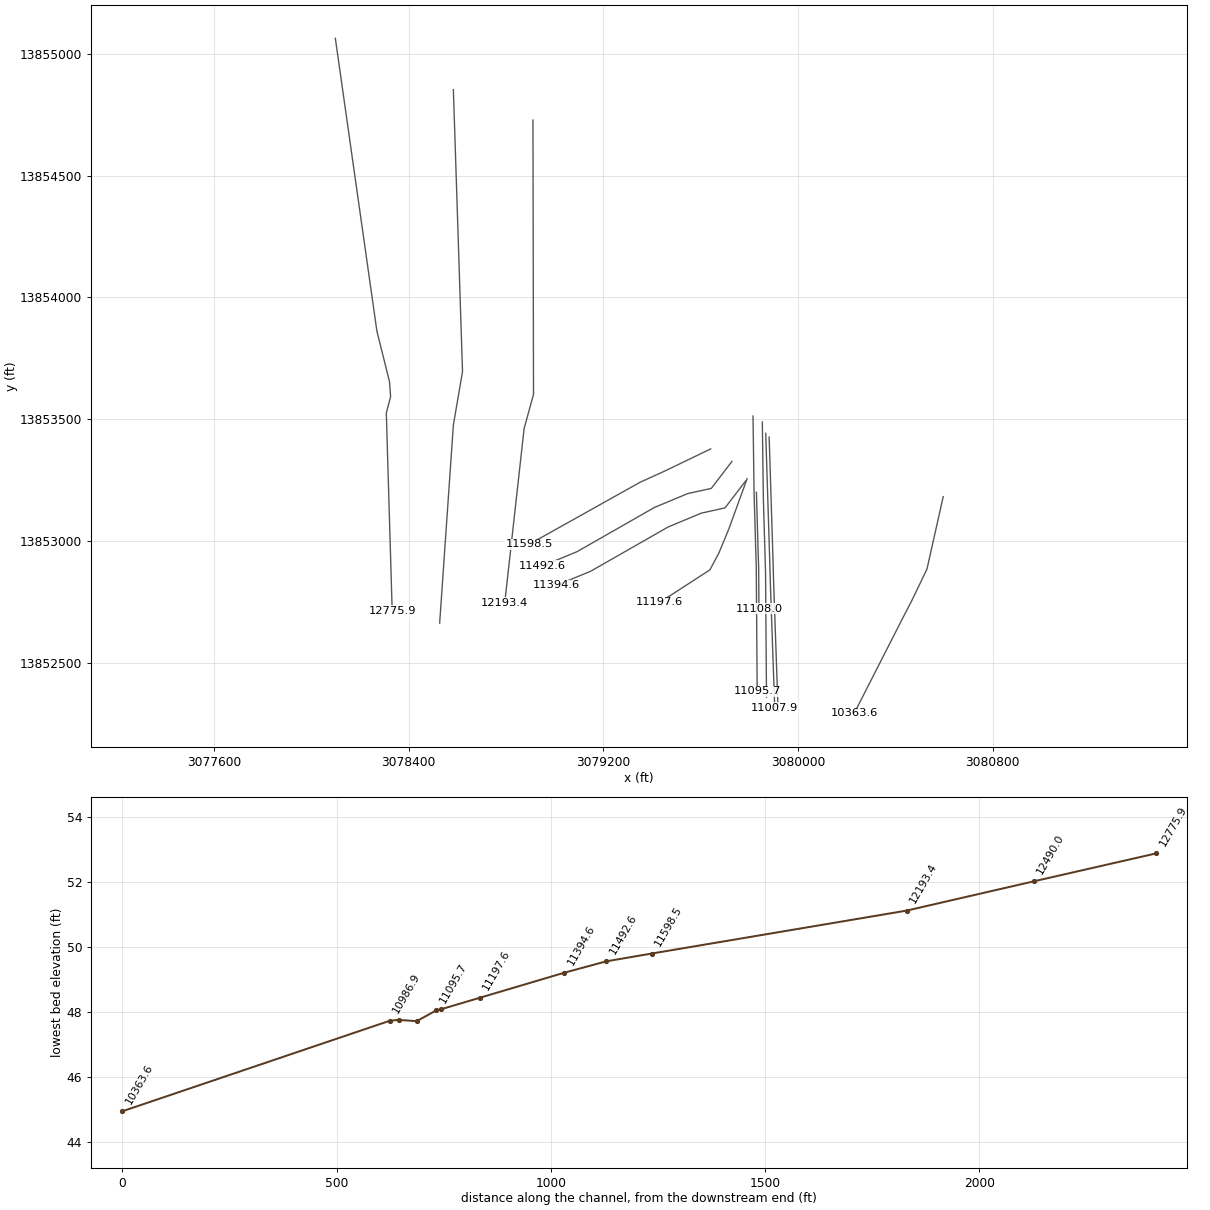
HEC-RAS study W140-00-00.PRJ: W140-00-00

--- W140-00-00.g01 (geometry) --- (continued)

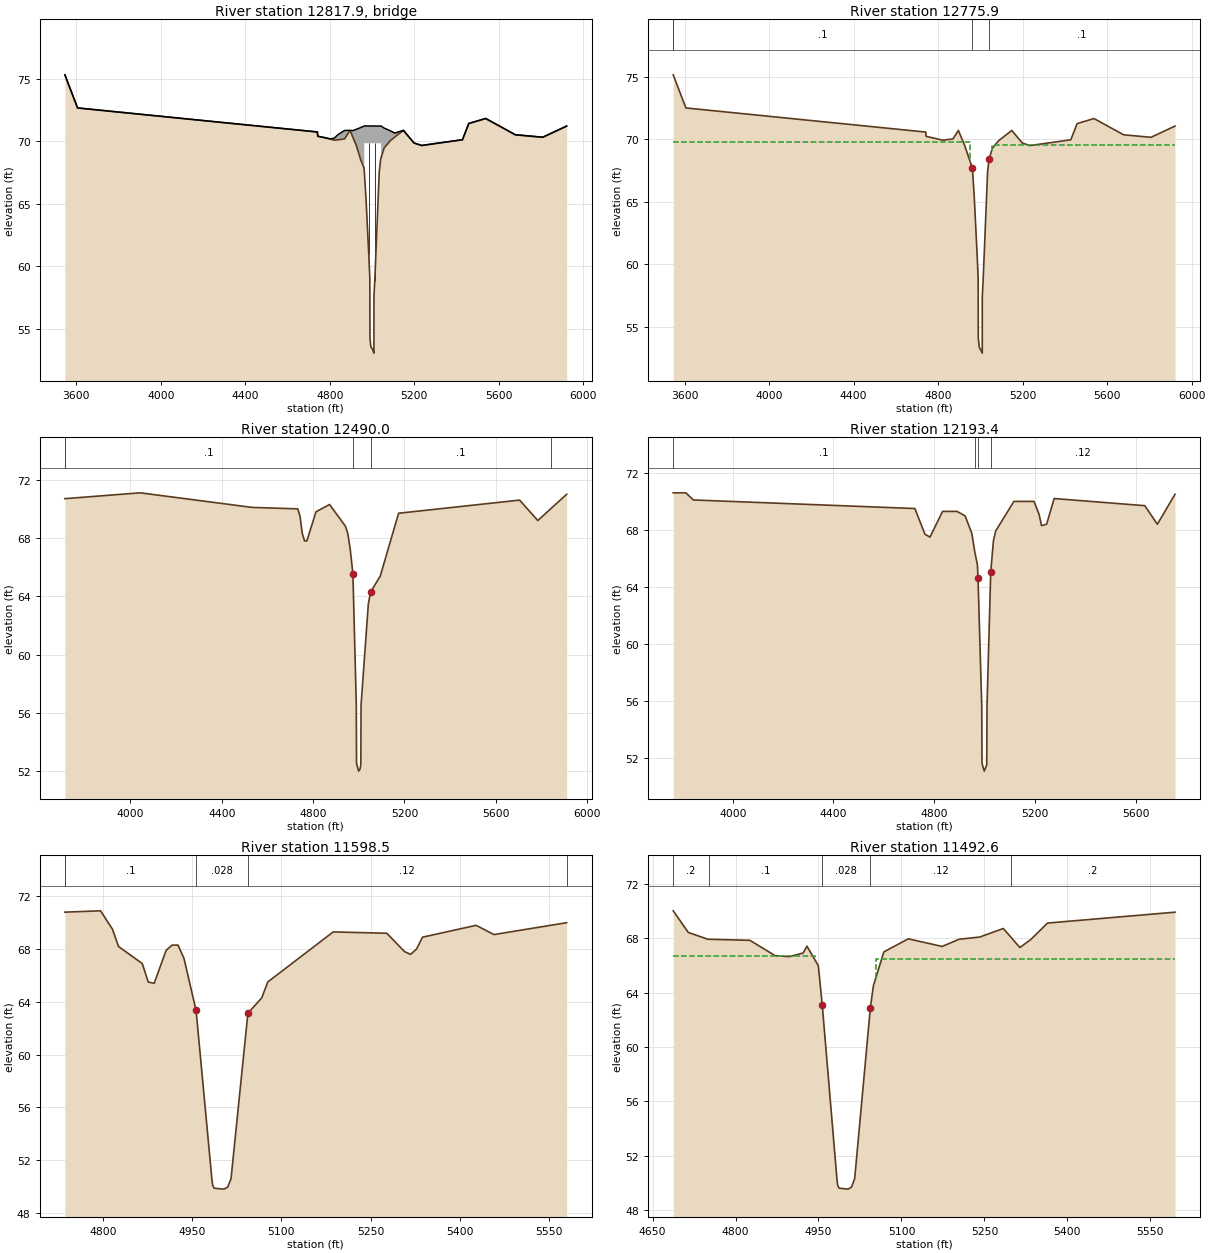
Type RM Length L Ch R = 3 ,12817.9 ,,,
BEGIN DESCRIPTION:
BINGLE ROAD
Structure ID: W40-15
END DESCRIPTION:
Bridge Culvert--1,0,-1,-1, 0
Deck Dist Width WeirC Skew NumUp NumDn MinLoCord MaxHiCord MaxSubmerge Is_Ogee
10,64,2.6,0, 29, 29, , , 0.95, 0, 1,1,,
  3546.1  3606.1  4741.6  4742.8  4802.5  4821.6  4838.6  4870.2  4895.9  4910.7
  4925.5  4946.4  4962.3 4963.21  4963.3 5043.19  5043.3  5057.1  5086.6  5107.6
  5148.6  5198.6  5234.8    5428    5458    5538    5678    5808  5921.2
    75.3   72.65   70.73   70.39   70.17   70.24   70.51   70.85   70.85   70.84
   70.94   71.08    71.2   71.21   71.21    71.2    71.2   71.04   70.82   70.64
   70.86   69.85   69.65   70.11   71.41   71.81   70.51   70.31    71.2
    75.3   72.65   70.72   70.38   70.16   70.07    70.1   70.17   70.85   70.25
   69.65    68.5   67.83   67.59   69.83   69.82   68.68   69.44   70.03   70.32
   70.85   69.84   69.64    70.1    71.4    71.8    70.5    70.3    71.2
  3546.1  3606.1  4741.6  4742.8  4802.5  4821.6  4838.6  4870.2  4895.9  4910.7
  4925.5  4946.4  4962.3 4963.21  4963.3 5043.19  5043.3  5057.1  5086.6  5107.6
  5148.6  5198.6  5234.8    5428    5458    5538    5678    5808  5921.2
    75.3   72.65   70.73   70.39   70.17   70.24   70.51   70.85   70.85   70.84
   70.94   71.08    71.2   71.21   71.21    71.2    71.2   71.04   70.82   70.64
   70.86   69.85   69.65   70.11   71.41   71.81   70.51   70.31    71.2
   75.17   72.52   70.59   70.25   70.03   69.94   69.97   70.04   70.72   70.12
   69.52   68.37    67.7   67.46    69.7   69.69   68.55   69.31    69.9   70.19
   70.72   69.71   69.51   69.97   71.27   71.67   70.37   70.17   71.07
Pier Skew, UpSta & Num, DnSta & Num=  ,4984.4, 2 ,4984.4, 2 , 0 , 0 , 0 ,,
     1.3     1.3
   59.75   70.83
     1.3     1.3
   59.62    70.7
Pier Skew, UpSta & Num, DnSta & Num=  ,5013, 2 ,5013, 2 , 0 , 0 , 0 ,,
     1.3     1.3
   57.63   70.82
     1.3     1.3
    57.5   70.69
Abutment Skew #Up #Dn= , 2 , 2
  4963.1  4989.7
   69.83   58.04
  4963.1  4989.7
    69.7   57.91
Abutment Skew #Up #Dn= , 2 , 2
  5009.1 5043.39
    57.6   69.82
  5009.1 5043.39
   57.47   69.69
BR Coef= 1 , 1 , 0 ,1.25, 0 ,,,0.8,0,2,0,
WSPro=,,,, 1 ,,,, 0 ,,,, 0 ,,,,-1 ,-1 ,-1 , 0 , 0 , 0 , 0 , 0
BR U #Sta/Elev= 71
  3546.1    75.3  3606.1   72.65  3939.2   72.08  4286.7   71.49  4516.7    71.1
  4576.7      71  4731.8   70.74  4741.6   70.72  4742.8   70.38  4765.1   70.31
  4779.7   70.26  4802.5   70.16  4821.6   70.07  4838.6    70.1  4870.2   70.17
    4871   70.19  4895.9   70.85  4910.7   70.25  4925.5   69.65 4928.19    69.5
  4928.3    69.5 4928.41   69.49  4943.2   68.68  4946.4    68.5  4962.3   67.83
  4963.1   67.62 4963.21   67.59  4963.3   67.57  4971.2   65.48  4984.4      61
  4989.6   58.99  4989.7   58.04  4990.1   54.26  4994.4   53.53  5002.1   53.35
  5008.9   53.03    5009   57.57  5009.1    57.6    5013   58.83  5034.2   67.55
  5040.7   68.54 5043.19   68.68  5043.3   68.68  5043.4   68.69  5057.1   69.44
  5067.9   69.66 5076.79   69.83  5076.9   69.84 5077.01   69.84  5086.6   70.03
  5096.2   70.16  5106.2    70.3  5107.6   70.32  5148.6   70.85  5149.4   70.83
  5198.6   69.84  5200.3   69.83  5234.8   69.64  5235.2   69.64  5317.3   69.84
    5428    70.1    5458    71.4    5538    71.8    5678    70.5  5807.3    70.3
    5808    70.3  5827.3   70.45  5837.3   70.53  5867.3   70.77  5910.4   71.11
  5921.2    71.2
BR U #Mann= 4
  3546.1      .2  3546.1      .1  4962.3    .025  5040.7      .1
BR U Banks=4962.3,5040.7
BR D #Sta/Elev= 71
  3546.1   75.17  3606.1   72.52  3939.2   71.95  4286.7   71.36  4516.7   70.97
  4576.7   70.87  4731.8   70.61  4741.6   70.59  4742.8   70.25  4765.1   70.18
  4779.7   70.13  4802.5   70.03  4821.6   69.94  4838.6   69.97  4870.2   70.04
    4871   70.06  4895.9   70.72  4910.7   70.12  4925.5   69.52 4928.19   69.37
  4928.3   69.37 4928.41   69.36  4943.2   68.55  4946.4   68.37  4962.3    67.7
  4963.1   67.49 4963.21   67.46  4963.3   67.44  4971.2   65.35  4984.4   60.87
  4989.6   58.86  4989.7   57.91  4990.1   54.13  4994.4    53.4  5002.1   53.22
  5008.9    52.9    5009   57.44  5009.1   57.47    5013    58.7  5034.2   67.42
  5040.7   68.41 5043.19   68.55  5043.3   68.55  5043.4   68.56  5057.1   69.31
  5067.9   69.53 5076.79    69.7  5076.9   69.71 5077.01   69.71  5086.6    69.9
  5096.2   70.03  5106.2   70.17  5107.6   70.19  5148.6   70.72  5149.4    70.7
  5198.6   69.71  5200.3    69.7  5234.8   69.51  5235.2   69.51  5317.3   69.71
    5428   69.97    5458   71.27    5538   71.67    5678   70.37  5807.3   70.17
    5808   70.17  5827.3   70.32  5837.3    70.4  5867.3   70.64  5910.4   70.98
  5921.2   71.07
BR D #Mann= 4
  3546.1      .2  3546.1      .1  4962.3    .025  5040.7      .1
BR D Banks=4962.3,5040.7
BC Design=,, 0 ,, 0 ,,,,,,
BC HTab HWMax=75.33

Type RM Length L Ch R = 1 ,12775.9 ,285.9,285.9,285.9
BEGIN DESCRIPTION:
Downstream Section of Bridge/Culvert/Weir
END DESCRIPTION:
XS GIS Cut Line= 6
       3078098.8     13855064.93      3078269.51      13853862.4
      3078321.37     13853653.97      3078325.92     13853592.58
       3078308.3     13853525.18      3078332.44      13852711.8
#Sta/Elev= 30
  3546.1   75.14  3606.1   72.49  4741.6   70.56  4742.8   70.22  4821.6   69.91
  4870.2   70.01  4895.9   70.69  4925.5   69.49  4962.3   67.67  4971.2   65.32
  4984.4   60.84  4989.6   58.83  4990.1    54.1  4994.4   53.37  5008.9   52.87
    5009   57.41    5013   58.67  5034.2   67.39  5040.7   68.38  5057.1   69.28
  5086.6   69.87  5148.6   70.69  5198.6   69.68  5235.2   69.48    5428   69.94
    5458   71.24    5538   71.64    5678   70.34    5808   70.14  5921.2   71.04
#Mann= 4 , 1 , 0
  3546.1      .2       0  3546.1      .1       0  4962.3    .025       0
  5040.7      .1       0
#XS Ineff= 2 , 0
       0    4953    69.8  5053.2       0    69.5
Permanent Ineff=
       F       F
Bank Sta=4962.3,5040.7
Exp/Cntr=0.5,0.3

Type RM Length L Ch R = 1 ,12490.0 ,308.8,296.6,290.8
BEGIN DESCRIPTION:
Cross Section 12490.0-Interpolated
END DESCRIPTION:
XS GIS Cut Line= 4
      3078583.87     13854854.22      3078621.45     13853695.47
      3078583.87     13853476.25       3078527.5     13852661.99
#Sta/Elev= 28
  3712.6    70.7  4042.6    71.1  4532.6    70.1  4732.6      70  4742.6    69.5
  4752.6    68.3  4762.6    67.8  4772.6    67.8  4812.6    69.8    4872    70.3
    4942    68.8    4952    68.3    4962    67.3  4974.3   65.55  4989.1   56.59
  4990.2   52.55  4999.1   52.01  5005.2   52.14    5009   52.45    5010   56.55
    5042    63.5    5052    64.3  5094.4    65.4  5174.4    69.7  5704.4    70.6
  5784.4    69.2  5843.8   70.05  5910.6      71
#Mann= 5 , 1 , 0
  3712.6      .2       0  3712.6      .1       0  4974.3    .022       0
    5052      .1       0  5843.8      .2       0
Bank Sta=4974.3,5052
Exp/Cntr=0.3,0.1

Type RM Length L Ch R = 1 ,12193.4 ,646.7,594.9,491.4
BEGIN DESCRIPTION:
Cross Section 12193.4
END DESCRIPTION:
XS GIS Cut Line= 4
      3078910.89     13854729.06      3078913.14     13853601.96
      3078874.49     13853460.99      3078794.96     13852745.36
#Sta/Elev= 30
  3763.5    70.6  3813.5    70.6  3843.5    70.1  4723.5    69.5  4763.5    67.7
  4783.5    67.5  4833.5    69.3  4890.6    69.3  4922.9   68.99  4949.6   67.77
  4961.8   66.43  4971.9   65.57  4974.3   64.65  4989.1   55.69  4990.2   51.65
  4999.1   51.11    5009   51.55    5010   55.65  5024.9   65.08  5035.8   67.28
  5044.6   67.93  5116.8      70  5196.8      70  5216.8    69.1  5226.8    68.3
  5246.8    68.4  5276.8    70.2  5636.8    69.7  5686.8    68.4  5756.8    70.5
#Mann= 4 , 1 , 0
  3763.5      .1       0  4961.8     .12       0  4974.3    .028       0
  5024.9     .12       0
Bank Sta=4974.3,5024.9
Exp/Cntr=0.3,0.1

Type RM Length L Ch R = 1 ,11598.5 ,100.7,105.9,107.4
BEGIN DESCRIPTION:
Cross Section 11598.5-Interpolated
END DESCRIPTION:
XS GIS Cut Line= 4
      3079641.12     13853377.79      3079456.33     13853288.58
      3079351.18     13853240.79      3078895.57      13852985.9
#Sta/Elev= 30
  4736.4    70.8  4796.4    70.9  4816.4    69.5  4826.4    68.2  4866.4    66.9
  4876.4    65.5  4886.4    65.4  4906.4    67.9  4916.4    68.3  4926.4    68.3
  4936.4    67.3  4956.8   63.34  4983.5   50.46  4984.8   50.06  4987.1   49.86
  5003.5   49.79  5009.8   49.94  5015.5   50.58  5043.8   63.13  5067.1    64.3
  5077.1    65.5  5187.1    69.3  5277.1    69.2  5307.1    67.8  5317.1    67.6
  5327.1      68  5337.1    68.9  5427.1    69.8  5457.1    69.1  5579.2      70
#Mann= 5 , 1 , 0
  4736.4      .2       0  4736.4      .1       0  4956.8    .028       0
  5043.8     .12       0  5579.2      .2       0
Bank Sta=4956.8,5043.8
Exp/Cntr=0.5,0.3

Type RM Length L Ch R = 1 ,11492.6 ,98,98,98
BEGIN DESCRIPTION:
Upstream Section of Bridge/Culvert/Weir
END DESCRIPTION:
XS GIS Cut Line= 6
      3079728.25     13853326.06      3079643.76      13853215.6
      3079546.68     13853194.12      3079410.25     13853137.27
      3079091.89     13852955.44      3078950.35     13852896.93
#Sta/Elev= 29
  4687.4   70.02  4714.6   68.43    4750   67.93  4826.2   67.85  4871.6   66.72
  4897.7   66.65  4922.4   66.92  4929.1   67.42  4949.7   65.99  4956.8    63.1
  4983.5   50.22  4984.8   49.82  4987.1   49.62  5003.5   49.55  5009.8    49.7
  5015.5   50.34  5043.8   62.89  5049.3   64.51  5068.2      67  5112.3   67.96
  5173.6    67.4  5204.4   67.93  5241.4   68.09  5284.1   68.72  5297.9   68.08
  5314.1   67.32  5334.1   67.92  5364.1   69.12  5594.5   69.92
#Mann= 5 , 1 , 0
  4687.4      .2       0  4751.9      .1       0  4956.8    .028       0
  5043.8     .12       0  5297.9      .2       0
#XS Ineff= 2 , 0
       0    4943    66.7  5053.5       0    66.5
Permanent Ineff=
       F       F
Bank Sta=4956.8,5043.8
Exp/Cntr=0.5,0.3

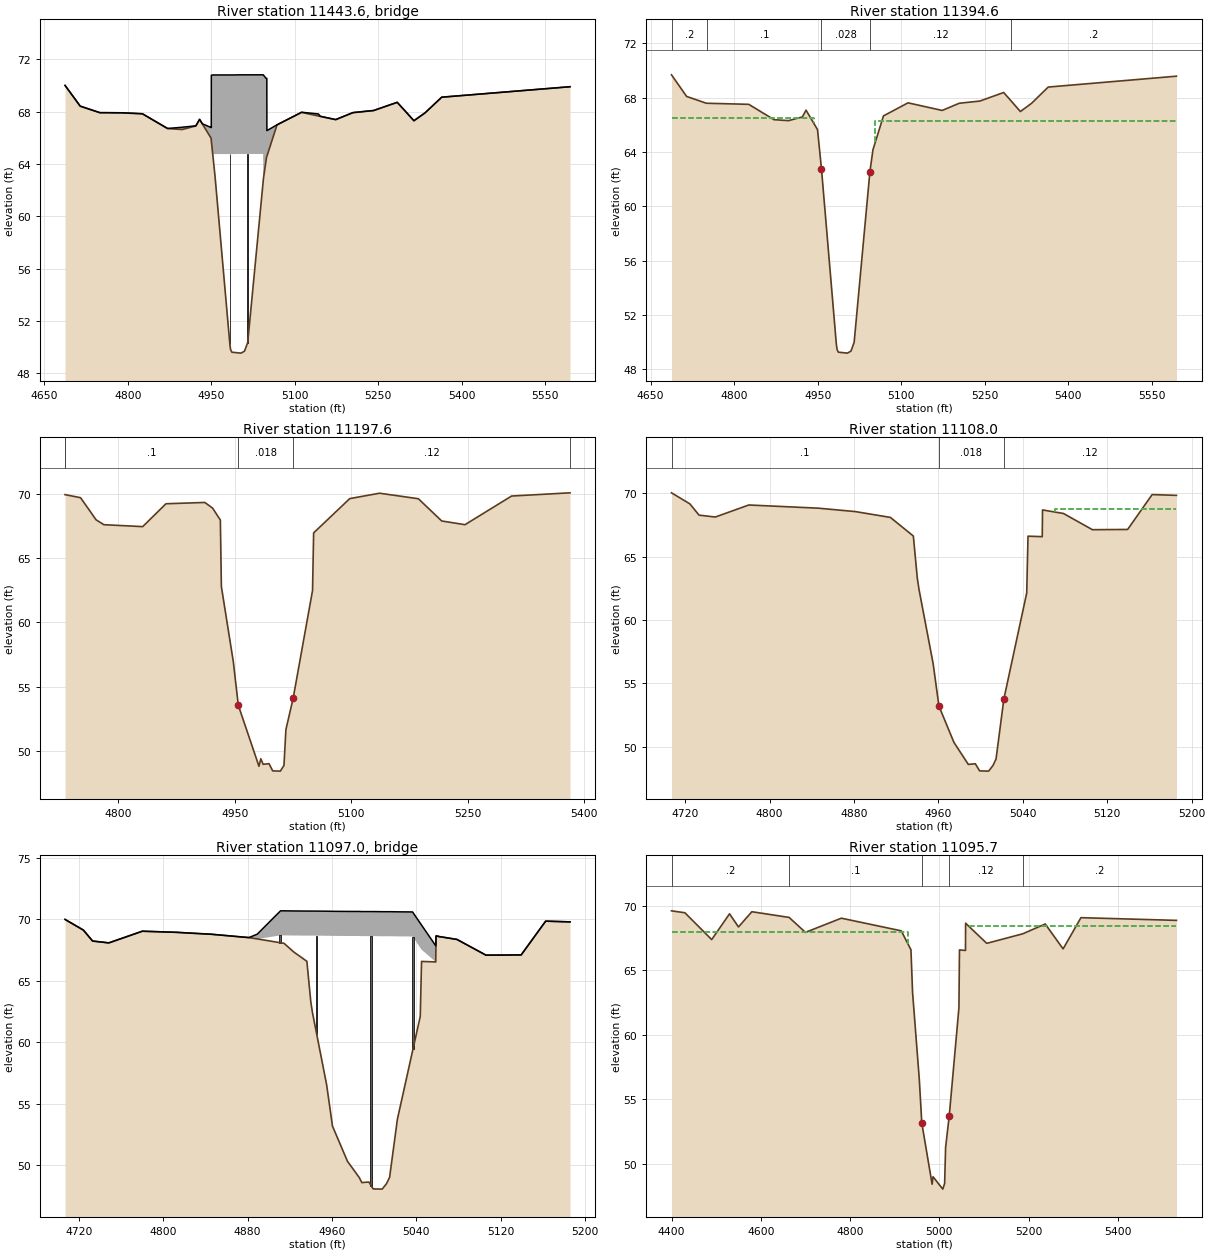
Type RM Length L Ch R = 3 ,11443.6 ,,,
BEGIN DESCRIPTION:
WESTVIEW ROAD
Structure ID: W40-14
END DESCRIPTION:
Bridge Culvert--1,0,-1,-1, 0
Deck Dist Width WeirC Skew NumUp NumDn MinLoCord MaxHiCord MaxSubmerge Is_Ogee
10,78,2.6,0, 60, 60, , , 0.95, 0, 1,1,,
  4687.4  4703.5  4714.6    4750  4758.2  4790.1  4790.3  4824.5  4826.2    4870
  4871.6  4897.7    4899  4922.4  4929.1    4934  4949.7 4950.09  4950.2 4950.31
  4953.3 4953.41  4953.5  4953.6  4956.8  4983.5  4984.8  4987.1  5003.5  5009.8
  5015.3  5015.5  5043.2 5043.29  5043.4  5043.5  5043.8  5048.4  5049.3 5049.79
  5049.9 5050.01  5068.2  5077.8  5107.4  5112.3  5142.5    5146  5173.6  5204.4
  5205.9  5238.1  5241.4  5284.1  5289.9  5297.9  5314.1  5334.1  5364.1  5594.5
      70   69.07   68.42   67.92   67.92   67.91   67.91   67.84   67.84   66.75
   66.71    66.8   66.81   66.91   67.41   67.07   66.78   66.78   70.78   70.78
    70.8    70.8    70.8    70.8    70.8    70.8    70.8    70.8   70.81   70.81
   70.81   70.81   70.81   70.81   70.81    70.8   70.79   70.55   70.54   70.54
   70.54   66.54   66.99    67.2   67.84   67.95   67.82   67.64   67.39   67.92
   67.93   68.07   68.08   68.71   68.44   68.07    67.3    67.9    69.1    69.9
      70   69.06   68.41   67.91   67.91    67.9    67.9   67.83   67.83   66.74
    66.7   66.63   66.64    66.9    67.4   67.06   65.97   65.81   65.77   65.72
    64.5   64.46   64.75   64.75   64.75   64.75   64.75   64.75   64.76   64.76
   64.76   64.76   64.76   64.76   62.69   62.74   62.87   64.22   64.49   64.55
   64.57   64.58   66.98   67.19   67.83   67.94   67.66   67.63   67.38   67.91
   67.92   68.06   68.07    68.7   68.43   68.06    67.3    67.9    69.1    69.9
  4687.4  4703.5  4714.6    4750  4758.2  4790.1  4790.3  4824.5  4826.2    4870
  4871.6  4897.7    4899  4922.4  4929.1    4934  4949.7 4950.09  4950.2 4950.31
  4953.3 4953.41  4953.5  4953.6  4956.8  4983.5  4984.8  4987.1  5003.5  5009.8
  5015.3  5015.5  5043.2 5043.29  5043.4  5043.5  5043.8  5048.4  5049.3 5049.79
  5049.9 5050.01  5068.2  5077.8  5107.4  5112.3  5142.5    5146  5173.6  5204.4
  5205.9  5238.1  5241.4  5284.1  5289.9  5297.9  5314.1  5334.1  5364.1  5594.5
      70   69.07   68.42   67.92   67.92   67.91   67.91   67.84   67.84   66.75
   66.71    66.8   66.81   66.91   67.41   67.07   66.78   66.78   70.78   70.78
    70.8    70.8    70.8    70.8    70.8    70.8    70.8    70.8   70.81   70.81
   70.81   70.81   70.81   70.81   70.81    70.8   70.79   70.55   70.54   70.54
   70.54   66.54   66.99    67.2   67.84   67.95   67.82   67.64   67.39   67.92
   67.93   68.07   68.08   68.71   68.44   68.07    67.3    67.9    69.1    69.9
   69.71   68.77   68.12   67.62   67.62   67.61   67.61   67.54   67.54   66.45
   66.41   66.34   66.35   66.61   67.11   66.77   65.68   65.52   65.48   65.43
   64.21   64.17   64.46   64.46   64.46   64.46   64.46   64.46   64.47   64.47
   64.47   64.47   64.47   64.47    62.4   62.45   62.58   63.93    64.2   64.26
   64.28   64.29   66.69    66.9   67.54   67.65   67.37   67.34   67.09   67.62
   67.63   67.77   67.78   68.41   68.14   67.77   67.01   67.61   68.81   69.61
Pier Skew, UpSta & Num, DnSta & Num=  ,4983.5, 2 ,4983.5, 2 , 0 , 0 , 0 ,,
     1.3     1.3
      49   65.75
     1.3     1.3
   48.71   65.46
Pier Skew, UpSta & Num, DnSta & Num=  ,5015.5, 2 ,5015.5, 2 , 0 , 0 , 0 ,,
     1.4     1.4
   49.25   65.76
     1.4     1.4
   48.96   65.47
BR Coef= 1 , 1 , 0 ,1.25, 0 ,,,0.8,0,2,0,
WSPro=,,,, 1 ,,,, 0 ,,,, 0 ,,,,-1 ,-1 ,-1 , 0 , 0 , 0 , 0 , 0
BR U #Sta/Elev= 60
  4687.4      70  4703.5   69.06  4714.6   68.41    4750   67.91  4758.2   67.91
  4790.1    67.9  4790.3    67.9  4824.5   67.83  4826.2   67.83    4870   66.74
  4871.6    66.7  4897.7   66.63    4899   66.64  4922.4    66.9  4929.1    67.4
    4934   67.06  4949.7   65.97 4950.09   65.81  4950.2   65.77 4950.31   65.72
  4953.3    64.5 4953.41   64.46  4953.5   64.42  4953.6   64.38  4956.8   63.08
  4983.5    50.2  4984.8    49.8  4987.1    49.6  5003.5   49.53  5009.8   49.68
  5015.3   50.31  5015.5   50.32  5043.2    62.6 5043.29   62.64  5043.4   62.69
  5043.5   62.74  5043.8   62.87  5048.4   64.22  5049.3   64.49 5049.79   64.55
  5049.9   64.57 5050.01   64.58  5068.2   66.98  5077.8   67.19  5107.4   67.83
  5112.3   67.94  5142.5   67.66    5146   67.63  5173.6   67.38  5204.4   67.91
  5205.9   67.92  5238.1   68.06  5241.4   68.07  5284.1    68.7  5289.9   68.43
  5297.9   68.06  5314.1    67.3  5334.1    67.9  5364.1    69.1  5594.5    69.9
BR U #Mann= 5
  4687.4      .2  4751.9      .1  4956.8    .028  5043.8     .12  5297.9      .2
BR U Banks=4956.8,5043.8
BR D #Sta/Elev= 60
  4687.4   69.71  4703.5   68.77  4714.6   68.12    4750   67.62  4758.2   67.62
  4790.1   67.61  4790.3   67.61  4824.5   67.54  4826.2   67.54    4870   66.45
  4871.6   66.41  4897.7   66.34    4899   66.35  4922.4   66.61  4929.1   67.11
    4934   66.77  4949.7   65.68 4950.09   65.52  4950.2   65.48 4950.31   65.43
  4953.3   64.21 4953.41   64.17  4953.5   64.13  4953.6   64.09  4956.8   62.79
  4983.5   49.91  4984.8   49.51  4987.1   49.31  5003.5   49.24  5009.8   49.39
  5015.3   50.02  5015.5   50.03  5043.2   62.31 5043.29   62.35  5043.4    62.4
  5043.5   62.45  5043.8   62.58  5048.4   63.93  5049.3    64.2 5049.79   64.26
  5049.9   64.28 5050.01   64.29  5068.2   66.69  5077.8    66.9  5107.4   67.54
  5112.3   67.65  5142.5   67.37    5146   67.34  5173.6   67.09  5204.4   67.62
  5205.9   67.63  5238.1   67.77  5241.4   67.78  5284.1   68.41  5289.9   68.14
  5297.9   67.77  5314.1   67.01  5334.1   67.61  5364.1   68.81  5594.5   69.61
BR D #Mann= 5
  4687.4      .2  4751.9      .1  4956.8    .028  5043.8     .12  5297.9      .2
BR D Banks=4956.8,5043.8
BC Design=,, 0 ,, 0 ,,,,,,
BC HTab HWMax=70.02

Type RM Length L Ch R = 1 ,11394.6 ,197,197,197
BEGIN DESCRIPTION:
Downstream Section of Bridge/Culvert/Weir
END DESCRIPTION:
XS GIS Cut Line= 6
      3079784.55     13853245.85      3079700.06      13853135.4
      3079602.98     13853113.92      3079466.55     13853057.07
      3079148.19     13852875.24      3079006.66     13852816.72
#Sta/Elev= 29
  4687.4   69.67  4714.6   68.08    4750   67.58  4826.2    67.5  4871.6   66.37
  4897.7    66.3  4922.4   66.57  4929.1   67.07  4949.7   65.64  4956.8   62.75
  4983.5   49.87  4984.8   49.47  4987.1   49.27  5003.5    49.2  5009.8   49.35
  5015.5   49.99  5043.8   62.54  5049.3   64.16  5068.2   66.65  5112.3   67.61
  5173.6   67.05  5204.4   67.58  5241.4   67.74  5284.1   68.37  5297.9   67.73
  5314.1   66.97  5334.1   67.57  5364.1   68.77  5594.5   69.57
#Mann= 5 , 1 , 0
  4687.4      .2       0  4751.9      .1       0  4956.8    .028       0
  5043.8     .12       0  5297.9      .2       0
#XS Ineff= 2 , 0
       0    4943    66.5  5053.5       0    66.3
Permanent Ineff=
       F       F
Bank Sta=4956.8,5043.8
Exp/Cntr=0.5,0.3

Type RM Length L Ch R = 1 ,11197.6 ,91.8,89.6,85.1
BEGIN DESCRIPTION:
Cross Section 11197.6-Interpolated
END DESCRIPTION:
XS GIS Cut Line= 5
       3079790.8     13853255.18       3079715.8     13853048.93
      3079674.89     13852949.88      3079638.01     13852880.72
       3079432.3     13852747.29
#Sta/Elev= 30
  4731.5   69.95  4751.5   69.71  4771.5   67.99  4781.5   67.61  4831.5   67.46
  4861.5   69.24  4911.5   69.34  4921.5    68.9  4931.5   67.97  4932.8    62.8
  4948.2   56.94  4954.6   53.56  4981.2   48.81  4983.6   49.39  4986.6   48.96
  4994.2   49.01  4998.9   48.45  5008.7   48.43  5013.4   48.87  5015.9   51.66
  5025.3   54.12  5050.2   62.49  5051.6   66.97  5098.1   69.64  5136.5   70.06
  5186.5   69.63  5216.5    67.9  5246.5   67.61  5306.5   69.84  5381.7   70.09
#Mann= 5 , 1 , 0
  4731.5      .2       0  4731.5      .1       0  4954.6    .018       0
  5025.3     .12       0  5381.7      .2       0
Bank Sta=4954.6,5025.3
Exp/Cntr=0.5,0.3

Type RM Length L Ch R = 1 ,11108.0 ,12.3,12.3,12.3
BEGIN DESCRIPTION:
Upstream Section of Bridge/Culvert/Weir
END DESCRIPTION:
XS GIS Cut Line= 5
      3079829.22     13853199.55      3079829.31     13853192.74
      3079836.73     13852937.78      3079838.26     13852892.83
      3079839.56     13852721.19
#Sta/Elev= 30
 4707.07   70.04 4724.47   69.17 4733.17   68.28 4748.58   68.13 4780.33   69.08
 4846.02   68.83 4881.25   68.56 4914.49    68.1 4936.24   66.63 4939.98   63.32
 4941.54   62.45 4954.94   56.59 4960.51   53.21 4974.69   50.35 4988.35   48.61
 4994.96   48.66 4999.05    48.1 5007.58   48.08 5011.67   48.52 5014.62   49.04
 5022.02   53.77 5043.68   62.14  5044.9   66.62 5058.39   66.58 5058.65   68.69
 5078.48   68.41 5105.97   67.13  5139.3   67.15 5162.52    69.9 5185.57   69.84
#Mann= 3 , 1 , 0
 4707.07      .1       0 4960.51    .018       0 5022.02     .12       0
#XS Ineff= 2 , 0
       0    4881    68.5    5070       0   68.75
Permanent Ineff=
       F       F
Bank Sta=4960.51,5022.02
Exp/Cntr=0.5,0.3

Type RM Length L Ch R = 3 ,11097.0 ,,,
BEGIN DESCRIPTION:
24" PIPELINE, SKEW ANGLE OF 30 DEGREES
END DESCRIPTION:
Bridge Culvert--1,0,-1,-1, 0
Deck Dist Width WeirC Skew NumUp NumDn MinLoCord MaxHiCord MaxSubmerge Is_Ogee
10,2,2.6,0, 41, 41, , , 0.95, 0, 1,1,,
 4707.07 4724.47 4733.17 4748.58 4780.33 4812.44 4846.02 4881.25 4889.23 4889.34
 4889.43 4911.27 4914.49  4923.8 4936.24 4939.98 4941.54 4954.94 4960.51 4974.69
 4985.74 4988.35 4994.96 4999.05 5007.58 5011.67 5014.62 5022.02 5036.37 5043.68
  5044.9 5058.39 5058.65 5060.26 5060.37 5060.47 5078.48 5105.97  5139.3 5162.52
 5185.57
      70   69.13   68.24   68.09   69.04   68.95   68.79   68.52    68.8   68.81
   68.82    70.7    70.7   70.69   70.68   70.68   70.68   70.67   70.66   70.65
   70.65   70.64   70.64   70.64   70.63   70.63   70.63   70.62   70.61   69.69
   69.54   67.85   68.66   68.64   68.64   68.62   68.37   67.09   67.11   69.86
    69.8
      70   69.13   68.24   68.09   69.04   68.95   68.79   68.52   68.41   68.41
   68.41    68.7    68.7   68.69   68.68   68.68   68.68   68.67   68.66   68.65
   68.65   68.64   68.64   68.64   68.63   68.63   68.63   68.62   68.61   67.69
   67.54   66.54   68.65   68.63   68.63   68.62   68.37   67.09   67.11   69.86
    69.8
 4707.07 4724.47 4733.17 4748.58 4780.33 4812.44 4846.02 4881.25 4889.23 4889.34
 4889.43 4911.27 4914.49  4923.8 4936.24 4939.98 4941.54 4954.94 4960.51 4974.69
 4985.74 4988.35 4994.96 4999.05 5007.58 5011.67 5014.62 5022.02 5036.37 5043.68
  5044.9 5058.39 5058.65 5060.26 5060.37 5060.47 5078.48 5105.97  5139.3 5162.52
 5185.57
      70   69.13   68.24   68.09   69.04   68.95   68.79   68.52    68.8   68.81
   68.82    70.7    70.7   70.69   70.68   70.68   70.68   70.67   70.66   70.65
   70.65   70.64   70.64   70.64   70.63   70.63   70.63   70.62   70.61   69.69
   69.54   67.85   68.66   68.64   68.64   68.62   68.37   67.09   67.11   69.86
    69.8
      70   69.13   68.24   68.09   69.04   68.95   68.79   68.52   68.41   68.41
   68.41    68.7    68.7   68.69   68.68   68.68   68.68   68.67   68.66   68.65
   68.65   68.64   68.64   68.64   68.63   68.63   68.63   68.62   68.61   67.69
   67.54   66.54   68.65   68.63   68.63   68.62   68.37   67.09   67.11   69.86
    69.8
Pier Skew, UpSta & Num, DnSta & Num=  ,4910.6, 2 ,4910.6, 2 , 0 , 0 , 0 ,,
     1.5     1.5
    67.1    69.7
     1.5     1.5
    67.1    69.7
Pier Skew, UpSta & Num, DnSta & Num=  ,4945.5, 2 ,4945.5, 2 , 0 , 0 , 0 ,,
     1.5     1.5
   59.33   69.68
     1.5     1.5
   59.33   69.68
Pier Skew, UpSta & Num, DnSta & Num=  ,4997.1, 2 ,4997.1, 2 , 0 , 0 , 0 ,,
     1.5     1.5
   47.23   69.64
     1.5     1.5
   47.23   69.64
Pier Skew, UpSta & Num, DnSta & Num=  ,5036.9, 2 ,5036.9, 2 , 0 , 0 , 0 ,,
     1.5     1.5
   58.19   69.61
     1.5     1.5
   58.19   69.61
BR Coef= 1 , 1 , 0 ,1.25, 0 ,,,0.8,0,2,0,
WSPro=,,,, 1 ,,,, 0 ,,,, 0 ,,,,-1 ,-1 ,-1 , 0 , 0 , 0 , 0 , 0
BR U #Sta/Elev= 41
 4707.07      70 4724.47   69.13 4733.17   68.24 4748.58   68.09 4780.33   69.04
 4812.44   68.95 4846.02   68.79 4881.25   68.52 4889.23   68.41 4889.34   68.41
 4889.43   68.41 4911.27    68.1 4914.49   68.06  4923.8   67.35 4936.24   66.59
 4939.98   63.28 4941.54   62.41 4954.94   56.55 4960.51   53.17 4974.69   50.31
 4985.74      49 4988.35   48.57 4994.96   48.62 4999.05   48.06 5007.58   48.04
 5011.67   48.48 5014.62      49 5022.02   53.73 5036.37   59.28 5043.68    62.1
  5044.9   66.58 5058.39   66.54 5058.65   68.65 5060.26   68.63 5060.37   68.63
 5060.47   68.62 5078.48   68.37 5105.97   67.09  5139.3   67.11 5162.52   69.86
 5185.57    69.8
BR U #Mann= 3
 4707.07      .1 4960.51    .018 5022.02     .12
BR U Banks=4960.51,5022.02
BR D #Sta/Elev= 41
 4707.07      70 4724.47   69.13 4733.17   68.24 4748.58   68.09 4780.33   69.04
 4812.44   68.95 4846.02   68.79 4881.25   68.52 4889.23   68.41 4889.34   68.41
 4889.43   68.41 4911.27    68.1 4914.49   68.06  4923.8   67.35 4936.24   66.59
 4939.98   63.28 4941.54   62.41 4954.94   56.55 4960.51   53.17 4974.69   50.31
 4985.74      49 4988.35   48.57 4994.96   48.62 4999.05   48.06 5007.58   48.04
 5011.67   48.48 5014.62      49 5022.02   53.73 5036.37   59.28 5043.68    62.1
  5044.9   66.58 5058.39   66.54 5058.65   68.65 5060.26   68.63 5060.37   68.63
 5060.47   68.62 5078.48   68.37 5105.97   67.09  5139.3   67.11 5162.52   69.86
 5185.57    69.8
BR D #Mann= 3
 4707.07      .1 4960.51    .018 5022.02     .12
BR D Banks=4960.51,5022.02
BC Design=,, 0 ,, 0 ,,,,,,
BC HTab HWMax=70.04

Type RM Length L Ch R = 1 ,11095.7 ,45.4,45.4,45.4
BEGIN DESCRIPTION:
Upstream Section of Bridge/Culvert/Weir
END DESCRIPTION:
XS GIS Cut Line= 5
      3079815.17       13853513.      3079819.46     13853199.05
      3079826.88     13852944.09      3079828.41     13852899.14
      3079832.33     13852382.18
#Sta/Elev= 30
  4399.9   69.61  4429.9   69.46  4489.9   67.38  4529.9   69.38  4549.9   68.36
  4579.9   69.54  4663.3    69.1  4699.9   67.94 4780.33   69.04 4914.48   68.06
 4936.23   66.59 4939.87   63.28 4954.93   56.55  4960.5   53.17 4983.64   48.42
 4985.73      49 5007.57   48.04 5011.66   48.48 5013.83   51.27 5022.01   53.73
 5043.67    62.1 5044.89   66.58 5058.36   66.54 5058.64   68.65 5105.97   67.09
  5186.8   67.83    5237   68.59    5277   66.66    5317   69.08  5530.9   68.87
#Mann= 5 , 1 , 0
  4399.9      .2       0  4663.3      .1       0  4960.5    .025       0
 5022.01     .12       0  5186.8      .2       0
#XS Ineff= 2 , 0
       0    4930      68    5068       0    68.4
Permanent Ineff=
       F       F
Bank Sta=4960.5,5022.01
Exp/Cntr=0.5,0.3

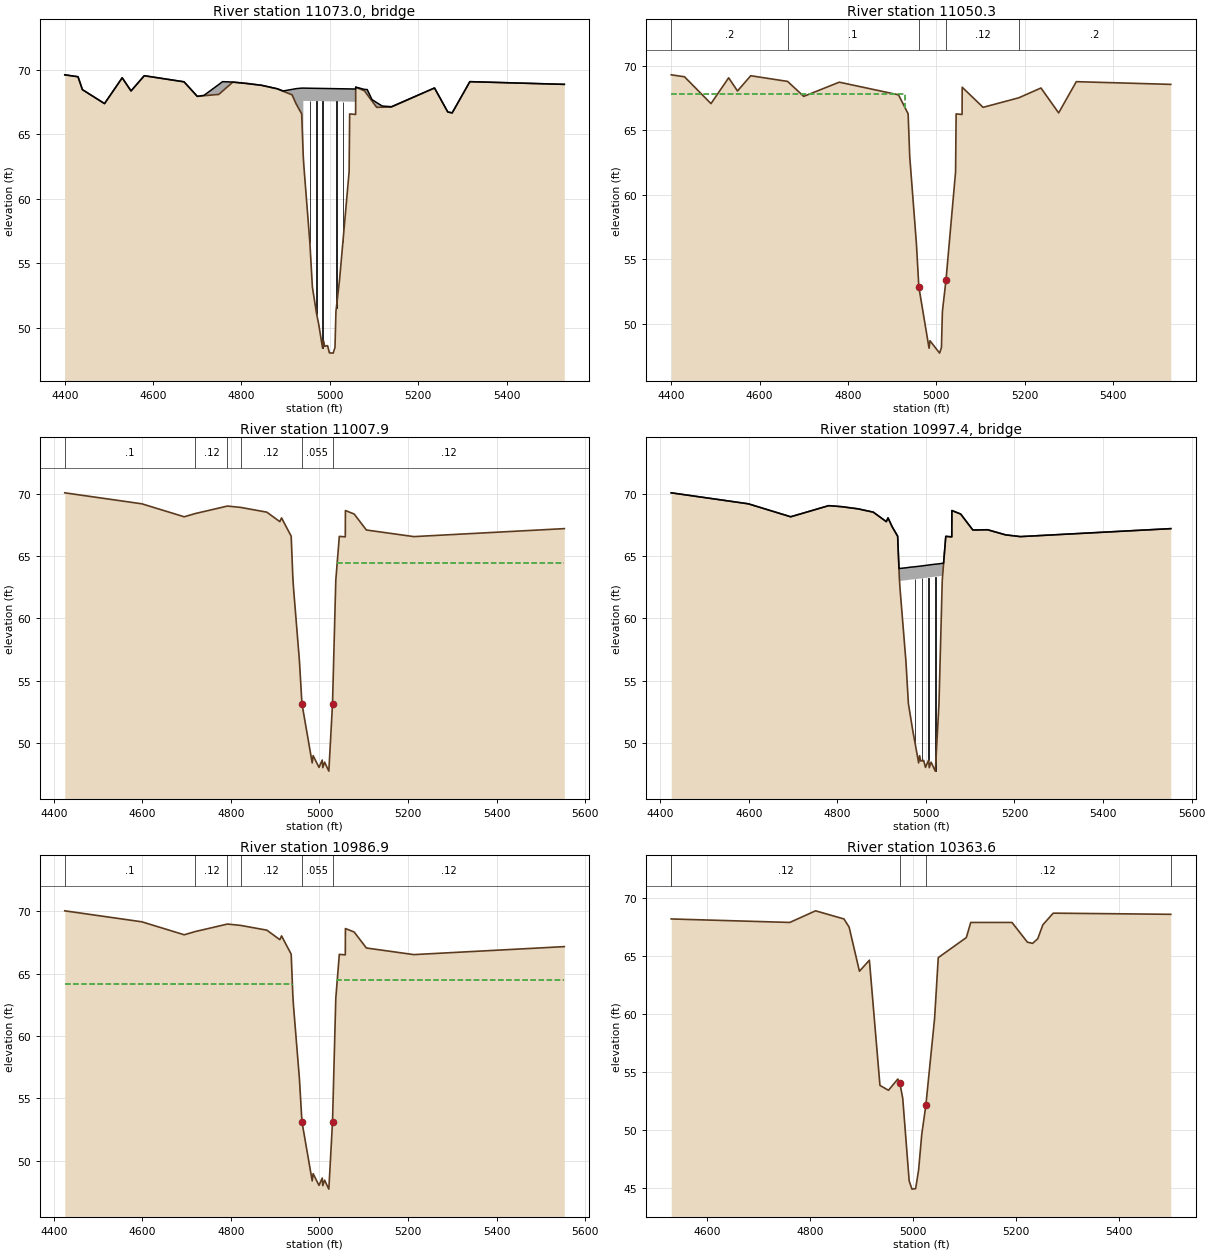
Type RM Length L Ch R = 3 ,11073.0 ,,,
BEGIN DESCRIPTION:
PECH ROAD, SKEW ANGLE OF 30 DEGREES
Structure ID: W40-13
END DESCRIPTION:
Bridge Culvert--1,0,-1,-1, 0
Deck Dist Width WeirC Skew NumUp NumDn MinLoCord MaxHiCord MaxSubmerge Is_Ogee
10,25.4,2.6,0, 34, 34, , , 0.95, 0, 1,1,,
  4399.9  4429.9  4439.9  4489.9  4529.9  4549.9  4579.9  4669.9  4699.9  4715.1
 4748.57  4757.1 4780.33 4846.01 4881.25  4894.1 4914.48 4923.79 4936.23 4939.97
 4940.06 5058.36 5058.64 5078.47  5084.6  5095.5 5105.97  5118.7 5139.29    5237
    5267    5277    5317  5530.9
   69.61   69.46   68.46   67.38   69.38   68.36   69.54   69.07   67.94   68.02
   68.86   69.08   69.05    68.8   68.53   68.36   68.48   68.54   68.58   68.58
   68.58   68.51   68.66   68.48   68.47   67.69   67.46   67.19   67.14   68.59
   66.73   66.66   69.08   68.87
   69.61   69.46   68.46   67.38   69.38   68.36   69.54   69.07   67.94   67.99
   68.09   68.35   69.04   68.79   68.52   68.34   68.06   67.35   66.59   63.23
   67.59   67.52   68.65   68.37   68.08   67.58   67.09    67.1   67.11   68.59
   66.73   66.66   69.08   68.87
  4399.9  4429.9  4439.9  4489.9  4529.9  4549.9  4579.9  4669.9  4699.9  4715.1
 4748.57  4757.1 4780.33 4846.01 4881.25  4894.1 4914.48 4923.79 4936.23 4939.97
 4940.06 5058.36 5058.64 5078.47  5084.6  5095.5 5105.97  5118.7 5139.29    5237
    5267    5277    5317  5530.9
   69.61   69.46   68.46   67.38   69.38   68.36   69.54   69.07   67.94   68.02
   68.86   69.08   69.05    68.8   68.53   68.36   68.48   68.54   68.58   68.58
   68.58   68.51   68.66   68.48   68.47   67.69   67.46   67.19   67.14   68.59
   66.73   66.66   69.08   68.87
   69.27   69.12   68.12   67.04   69.04   68.02    69.2   68.73    67.6   67.65
   67.75   68.01    68.7   68.45   68.18      68   67.72   67.01   66.25   62.89
   67.25   67.18   68.31   68.03   67.74   67.24   66.75   66.76   66.77   68.25
   66.39   66.32   68.74   68.53
Pier Skew, UpSta & Num, DnSta & Num=  ,4954.9, 2 ,4954.9, 2 , 0 , 0 , 0 ,,
       1       1
   55.24   68.59
       1       1
    54.9   68.25
Pier Skew, UpSta & Num, DnSta & Num=  ,4970.1, 2 ,4970.1, 2 , 0 , 0 , 0 ,,
       1       1
   49.99   68.59
       1       1
   49.65   68.25
Pier Skew, UpSta & Num, DnSta & Num=  ,4983.6, 2 ,4983.6, 2 , 0 , 0 , 0 ,,
       1       1
   47.52   68.58
       1       1
   47.18   68.24
Pier Skew, UpSta & Num, DnSta & Num=  ,5014.6, 2 ,5014.6, 2 , 0 , 0 , 0 ,,
       1       1
   50.36   68.58
       1       1
   50.02   68.24
Pier Skew, UpSta & Num, DnSta & Num=  ,5029.5, 2 ,5029.5, 2 , 0 , 0 , 0 ,,
       1       1
   55.43   68.57
       1       1
   55.09   68.23
Abutment Skew #Up #Dn= , 2 , 2
 5072.73 5073.78
   68.45   68.44
 5072.73 5073.78
   68.11    68.1
BR Coef= 1 , 1 , 0 ,1.25, 0 ,,,0.8,0,2,0,
WSPro=,,,, 1 ,,,, 0 ,,,, 0 ,,,,-1 ,-1 ,-1 , 0 , 0 , 0 , 0 , 0
BR U #Sta/Elev= 69
  4399.9   69.61  4429.9   69.46  4439.9   68.46  4489.9   67.38  4529.9   69.38
  4549.9   68.36  4579.9   69.54  4663.3    69.1  4669.9   69.07  4699.9   67.94
  4715.1   67.99 4748.57   68.09  4757.1   68.35 4780.33   69.04  4803.4   68.98
 4812.43   68.95 4846.01   68.79  4850.6   68.75 4881.25   68.52  4894.1   68.34
 4914.48   68.06 4923.79   67.35 4927.29   67.14  4927.4   67.13 4927.51   67.12
  4931.1    66.9 4936.23   66.59 4939.87   63.28 4939.97   63.23 4940.06   63.18
 4940.14   63.14 4941.54   62.41 4954.93   56.55  4960.5   53.17 4970.07   51.07
 4974.68   50.31 4983.64   48.42 4985.73      49 4988.34   48.57 4994.95   48.62
 4999.04   48.06 5007.57   48.04 5011.66   48.48 5013.83   51.27  5018.9   52.79
 5022.01   53.73 5043.67    62.1 5044.89   66.58 5058.36   66.54 5058.64   68.65
 5072.73   68.45 5073.58   68.44 5073.69   68.44 5078.47   68.37  5084.6   68.08
 5093.89   67.65    5094   67.65 5094.11   67.64  5095.5   67.58 5105.97   67.09
  5118.7    67.1 5139.29   67.11  5163.8   67.48  5186.8   67.83    5237   68.59
    5267   66.73    5277   66.66    5317   69.08  5530.9   68.87
BR U #Mann= 5
  4399.9      .2  4663.3      .1  4960.5    .025 5022.01     .12  5186.8      .2
BR U Banks=4960.5,5022.01
BR D #Sta/Elev= 69
  4399.9   69.27  4429.9   69.12  4439.9   68.12  4489.9   67.04  4529.9   69.04
  4549.9   68.02  4579.9    69.2  4663.3   68.76  4669.9   68.73  4699.9    67.6
  4715.1   67.65 4748.57   67.75  4757.1   68.01 4780.33    68.7  4803.4   68.64
 4812.43   68.61 4846.01   68.45  4850.6   68.41 4881.25   68.18  4894.1      68
 4914.48   67.72 4923.79   67.01 4927.29    66.8  4927.4   66.79 4927.51   66.78
  4931.1   66.56 4936.23   66.25 4939.87   62.94 4939.97   62.89 4940.06   62.84
 4940.14    62.8 4941.54   62.07 4954.93   56.21  4960.5   52.83 4970.07   50.73
 4974.68   49.97 4983.64   48.08 4985.73   48.66 4988.34   48.23 4994.95   48.28
 4999.04   47.72 5007.57    47.7 5011.66   48.14 5013.83   50.93  5018.9   52.45
 5022.01   53.39 5043.67   61.76 5044.89   66.24 5058.36    66.2 5058.64   68.31
 5072.73   68.11 5073.58    68.1 5073.69    68.1 5078.47   68.03  5084.6   67.74
 5093.89   67.31    5094   67.31 5094.11    67.3  5095.5   67.24 5105.97   66.75
  5118.7   66.76 5139.29   66.77  5163.8   67.14  5186.8   67.49    5237   68.25
    5267   66.39    5277   66.32    5317   68.74  5530.9   68.53
BR D #Mann= 5
  4399.9      .2  4663.3      .1  4960.5    .025 5022.01     .12  5186.8      .2
BR D Banks=4960.5,5022.01
BC Design=,, 0 ,, 0 ,,,,,,
BC HTab HWMax=69.61

Type RM Length L Ch R = 1 ,11050.3 ,42.4,42.4,42.4
BEGIN DESCRIPTION:
Downstream Section of Bridge/Culvert/Weir
END DESCRIPTION:
XS GIS Cut Line= 5
      3079853.39      13853488.5      3079857.68     13853174.55
       3079865.1     13852919.59      3079866.63     13852874.64
      3079870.55     13852357.68
#Sta/Elev= 30
  4399.9   69.28  4429.9   69.13  4489.9   67.05  4529.9   69.05  4549.9   68.03
  4579.9   69.21  4663.3   68.77  4699.9   67.61 4780.33   68.71 4914.48   67.73
 4936.23   66.26 4939.87   62.95 4954.93   56.22  4960.5   52.84 4983.64   48.09
 4985.73   48.67 5007.57   47.71 5011.66   48.15 5013.83   50.94 5022.01    53.4
 5043.67   61.77 5044.89   66.25 5058.36   66.21 5058.64   68.32 5105.97   66.76
  5186.8    67.5    5237   68.26    5277   66.33    5317   68.75  5530.9   68.54
#Mann= 5 , 1 , 0
  4399.9      .2       0  4663.3      .1       0  4960.5    .025       0
 5022.01     .12       0  5186.8      .2       0
#XS Ineff= 2 , 0
       0    4930    67.8    5068       0      67
Permanent Ineff=
       F       F
Bank Sta=4960.5,5022.01
Exp/Cntr=0.5,0.3

Type RM Length L Ch R = 1 ,11007.9 ,21,21,21
BEGIN DESCRIPTION:
Upstream Section of Bridge/Culvert/Weir
END DESCRIPTION:
XS GIS Cut Line= 4
       3079867.4     13853441.84      3079884.42     13852900.66
      3079884.92     13852870.69      3079904.31     13852314.58
#Sta/Elev= 30
 4425.02   70.06 4599.02   69.18 4694.72   68.14  4719.8    68.4  4792.4      69
  4822.2   68.89 4881.25   68.51 4910.57   67.75 4914.49   68.05 4936.24   66.58
 4939.98   63.27 4941.54    62.4 4954.94   56.54 4960.51   53.16 4983.65   48.41
 4985.74   48.99 4999.05   48.05 5006.27   48.64 5007.58   48.03 5011.67   48.47
 5021.24   47.75  5029.5   53.14  5036.9   63.04  5044.9   66.57 5058.39   66.53
 5058.65   68.64 5078.48   68.36 5105.97   67.08 5213.16   66.55 5552.89   67.19
#Mann= 6 , 1 , 0
 4425.02      .1       0  4719.8     .12       0  4792.4      .1       0
  4822.2     .12       0 4960.51    .055       0  5029.5     .12       0
#XS Ineff= 2 , 0
       0    4939   64.13    5040       0   64.47
Permanent Ineff=
       F       F
Bank Sta=4960.51,5029.5
Exp/Cntr=0.5,0.3

Type RM Length L Ch R = 3 ,10997.4 ,,,
BEGIN DESCRIPTION:
12" PIPELINE, SKEW ANGLE OF 30 DEGREES
END DESCRIPTION:
Bridge Culvert--1,0,-1,-1, 0
Deck Dist Width WeirC Skew NumUp NumDn MinLoCord MaxHiCord MaxSubmerge Is_Ogee
10,1,2.6,0, 46, 46, , , 0.95, 0, 1,1,,
 4425.02 4599.02 4694.72  4719.8 4780.33  4792.4 4812.44  4822.2 4846.02 4881.25
 4910.57 4914.49  4923.8 4936.24  4939.2 4939.98 4940.41  4940.5 4941.54 4954.94
 4960.51 4970.08  4971.3 4983.65 4985.74 4988.35 4994.96 4999.05 5006.27 5007.58
 5011.67 5021.24  5029.5  5036.9  5037.4 5037.51 5039.85  5044.9 5058.39 5058.65
 5078.48 5105.97  5139.3 5179.84 5213.16 5552.89
   70.07   69.19   68.15   68.41   69.04   69.01   68.95    68.9   68.79   68.52
   67.76   68.06   67.35   66.59      64      64      64   64.01   64.01   64.06
   64.09   64.13   64.13   64.18   64.19    64.2   64.23   64.25   64.28   64.29
   64.31   64.35   64.38   64.42   64.42   64.42   64.43   66.58   66.54   68.65
   68.37   67.09   67.11    66.7   66.56    67.2
   70.07   69.19   68.15   68.41   69.04   69.01   68.95    68.9   68.79   68.52
   67.76   68.06   67.35   66.59   63.97   63.28   63.04   63.01   63.01   63.06
   63.09   63.13   63.13   63.18   63.19    63.2   63.23   63.25   63.28   63.29
   63.31   63.35   63.38   63.42   63.42   63.32   64.35   66.58   66.54   68.65
   68.37   67.09   67.11    66.7   66.56    67.2
 4425.02 4599.02 4694.72  4719.8 4780.33  4792.4 4812.44  4822.2 4846.02 4881.25
 4910.57 4914.49  4923.8 4936.24  4939.2 4939.98 4940.41  4940.5 4941.54 4954.94
 4960.51 4970.08  4971.3 4983.65 4985.74 4988.35 4994.96 4999.05 5006.27 5007.58
 5011.67 5021.24  5029.5  5036.9  5037.4 5037.51 5039.85  5044.9 5058.39 5058.65
 5078.48 5105.97  5139.3 5179.84 5213.16 5552.89
   70.07   69.19   68.15   68.41   69.04   69.01   68.95    68.9   68.79   68.52
   67.76   68.06   67.35   66.59      64      64      64   64.01   64.01   64.06
   64.09   64.13   64.13   64.18   64.19    64.2   64.23   64.25   64.28   64.29
   64.31   64.35   64.38   64.42   64.42   64.42   64.43   66.58   66.54   68.65
   68.37   67.09   67.11    66.7   66.56    67.2
   70.07   69.19   68.15   68.41   69.04   69.01   68.95    68.9   68.79   68.52
   67.76   68.06   67.35   66.59   63.97   63.28   63.04   63.01   63.01   63.06
   63.09   63.13   63.13   63.18   63.19    63.2   63.23   63.25   63.28   63.29
   63.31   63.35   63.38   63.42   63.42   63.32   64.35   66.58   66.54   68.65
   68.37   67.09   67.11    66.7   66.56    67.2
Pier Skew, UpSta & Num, DnSta & Num=  ,4975.2, 2 ,4975.2, 2 , 0 , 0 , 0 ,,
       1       1
   48.97   64.15
       1       1
   48.97   64.15
Pier Skew, UpSta & Num, DnSta & Num=  ,4991.1, 2 ,4991.1, 2 , 0 , 0 , 0 ,,
       1       1
   47.59   64.21
       1       1
   47.59   64.21
Pier Skew, UpSta & Num, DnSta & Num=  ,5006.3, 2 ,5006.3, 2 , 0 , 0 , 0 ,,
       1       1
   47.42   64.28
       1       1
   47.42   64.28
Pier Skew, UpSta & Num, DnSta & Num=  ,5021.2, 2 ,5021.2, 2 , 0 , 0 , 0 ,,
       1       1
    46.8   64.35
       1       1
    46.8   64.35
BR Coef= 1 , 1 , 0 ,1.25, 0 ,,,0.8,0,2,0,
WSPro=,,,, 1 ,,,, 0 ,,,, 0 ,,,,-1 ,-1 ,-1 , 0 , 0 , 0 , 0 , 0
BR U #Sta/Elev= 46
 4425.02   70.07 4599.02   69.19 4694.72   68.15  4719.8   68.41 4780.33   69.04
  4792.4   69.01 4812.44   68.95  4822.2    68.9 4846.02   68.79 4881.25   68.52
 4910.57   67.76 4914.49   68.06  4923.8   67.35 4936.24   66.59  4939.2   63.97
 4939.98   63.28 4940.41   63.04  4940.5   62.99 4941.54   62.41 4954.94   56.55
 4960.51   53.17 4970.08   51.07  4971.3   50.83 4983.65   48.42 4985.74      49
 4988.35   48.57 4994.96   48.62 4999.05   48.06 5006.27   48.65 5007.58   48.04
 5011.67   48.48 5021.24   47.76  5029.5   53.15  5036.9   63.05  5037.4   63.27
 5037.51   63.32 5039.85   64.35  5044.9   66.58 5058.39   66.54 5058.65   68.65
 5078.48   68.37 5105.97   67.09  5139.3   67.11 5179.84    66.7 5213.16   66.56
 5552.89    67.2
BR U #Mann= 6
 4425.02      .1  4719.8     .12  4792.4      .1  4822.2     .12 4960.51    .055
  5029.5     .12
BR U Banks=4960.51,5029.5
BR D #Sta/Elev= 46
 4425.02   70.07 4599.02   69.19 4694.72   68.15  4719.8   68.41 4780.33   69.04
  4792.4   69.01 4812.44   68.95  4822.2    68.9 4846.02   68.79 4881.25   68.52
 4910.57   67.76 4914.49   68.06  4923.8   67.35 4936.24   66.59  4939.2   63.97
 4939.98   63.28 4940.41   63.04  4940.5   62.99 4941.54   62.41 4954.94   56.55
 4960.51   53.17 4970.08   51.07  4971.3   50.83 4983.65   48.42 4985.74      49
 4988.35   48.57 4994.96   48.62 4999.05   48.06 5006.27   48.65 5007.58   48.04
 5011.67   48.48 5021.24   47.76  5029.5   53.15  5036.9   63.05  5037.4   63.27
 5037.51   63.32 5039.85   64.35  5044.9   66.58 5058.39   66.54 5058.65   68.65
 5078.48   68.37 5105.97   67.09  5139.3   67.11 5179.84    66.7 5213.16   66.56
 5552.89    67.2
BR D #Mann= 6
 4425.02      .1  4719.8     .12  4792.4      .1  4822.2     .12 4960.51    .055
  5029.5     .12
BR D Banks=4960.51,5029.5
BC Design=,, 0 ,, 0 ,,,,,,
BC HTab HWMax=70.06

Type RM Length L Ch R = 1 ,10986.9 ,623.3,623.3,623.3
BEGIN DESCRIPTION:
Downstream Section of Bridge/Culvert/Weir
END DESCRIPTION:
XS GIS Cut Line= 4
      3079881.45     13853426.22      3079898.46     13852885.04
      3079898.96     13852855.07      3079918.35     13852298.96
#Sta/Elev= 30
 4425.02   70.03 4599.02   69.15 4694.72   68.11  4719.8   68.37  4792.4   68.97
  4822.2   68.86 4881.25   68.48 4910.57   67.72 4914.49   68.02 4936.24   66.55
 4939.98   63.24 4941.54   62.37 4954.94   56.51 4960.51   53.13 4983.65   48.38
 4985.74   48.96 4999.05   48.02 5006.27   48.61 5007.58      48 5011.67   48.44
 5021.24   47.72  5029.5   53.11  5036.9   63.01  5044.9   66.54 5058.39    66.5
 5058.65   68.61 5078.48   68.33 5105.97   67.05 5213.16   66.52 5552.89   67.16
#Mann= 6 , 1 , 0
 4425.02      .1       0  4719.8     .12       0  4792.4      .1       0
  4822.2     .12       0 4960.51    .055       0  5029.5     .12       0
#XS Ineff= 2 , 0
       0    4939   64.13    5040       0   64.47
Permanent Ineff=
       F       F
Bank Sta=4960.51,5029.5
Exp/Cntr=0.5,0.3

Type RM Length L Ch R = 1 ,10363.6 ,764.9,758.9,732.1
BEGIN DESCRIPTION:
Cross Section 10363.6
END DESCRIPTION:
XS GIS Cut Line= 5
      3080596.77     13853181.56       3080529.9     13852883.89
      3080466.17     13852751.55      3080438.88     13852699.25
       3080230.8     13852291.04
#Sta/Elev= 30
    4531    68.2    4761    67.9    4811    68.9  4866.1    68.2  4876.1    67.5
  4896.1    63.7  4915.4   64.65  4935.9   53.87  4952.4   53.45  4970.6   54.42
  4974.6   54.04  4980.1   52.76  4992.6   45.64    4998   44.94    5005   44.98
  5007.5   45.64  5010.9    46.6    5017   49.66  5024.9   52.14  5041.9   59.64
    5049   64.87  5103.5    66.6    5112    67.9    5192    67.9    5222    66.2
    5232    66.1    5242    66.5    5252    67.7    5272    68.7  5500.1    68.6
#Mann= 5 , 1 , 0
    4531      .2       0    4531     .12       0  4974.6    .055       0
  5024.9     .12       0  5500.1      .2       0
Bank Sta=4974.6,5024.9
Exp/Cntr=0.3,0.1