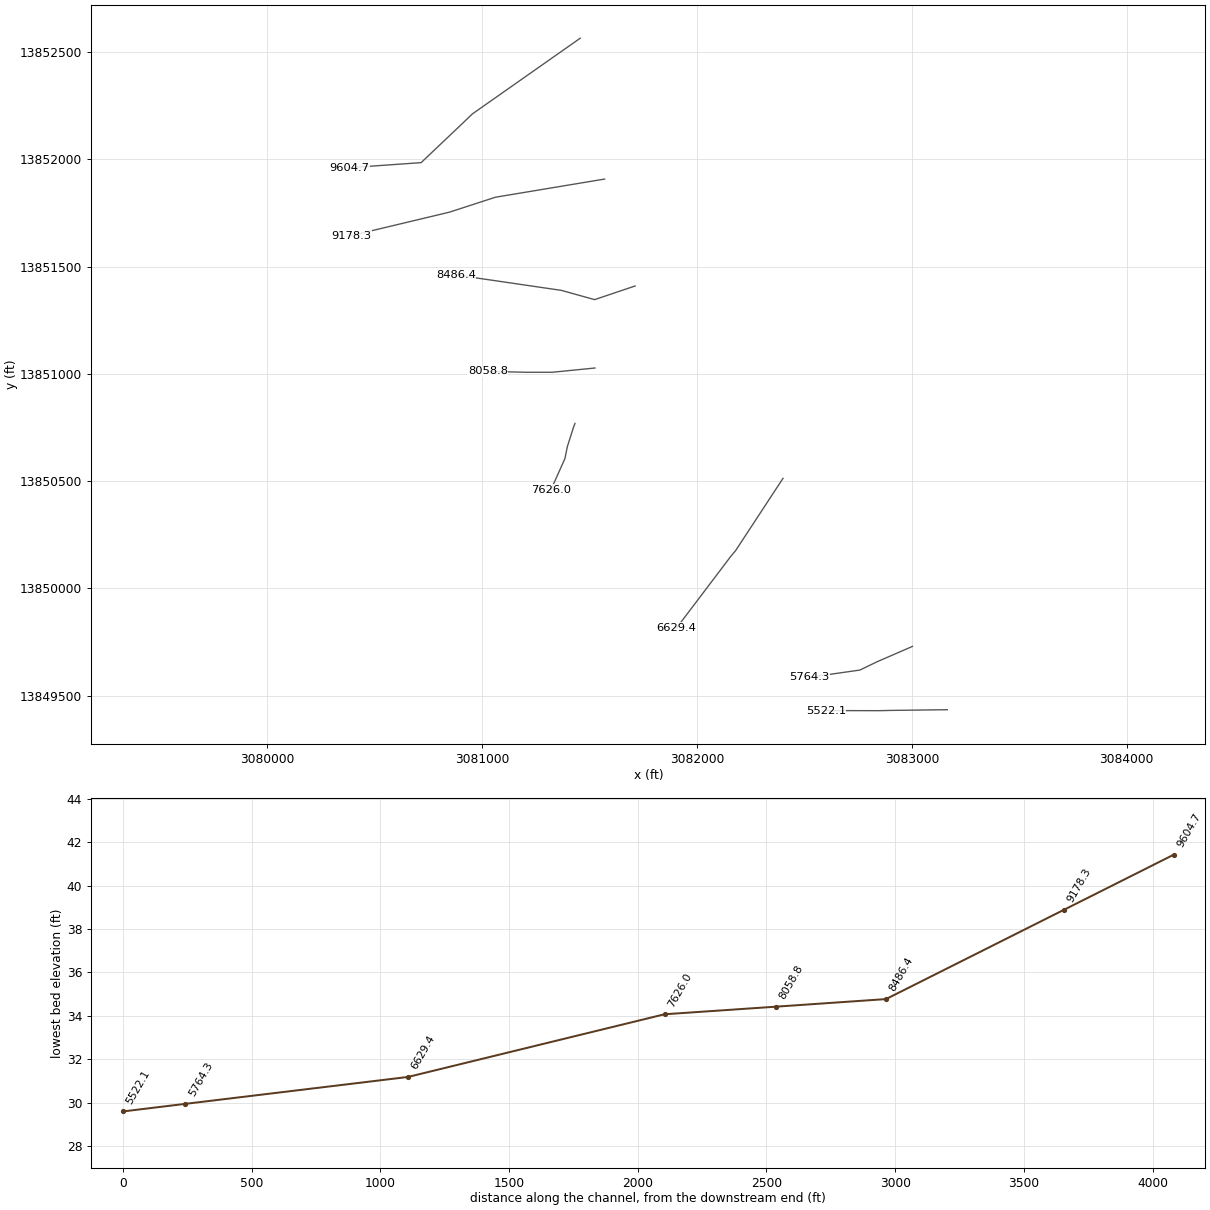
HEC-RAS study W140-00-00.PRJ: W140-00-00

--- W140-00-00.g01 (geometry) --- (continued)

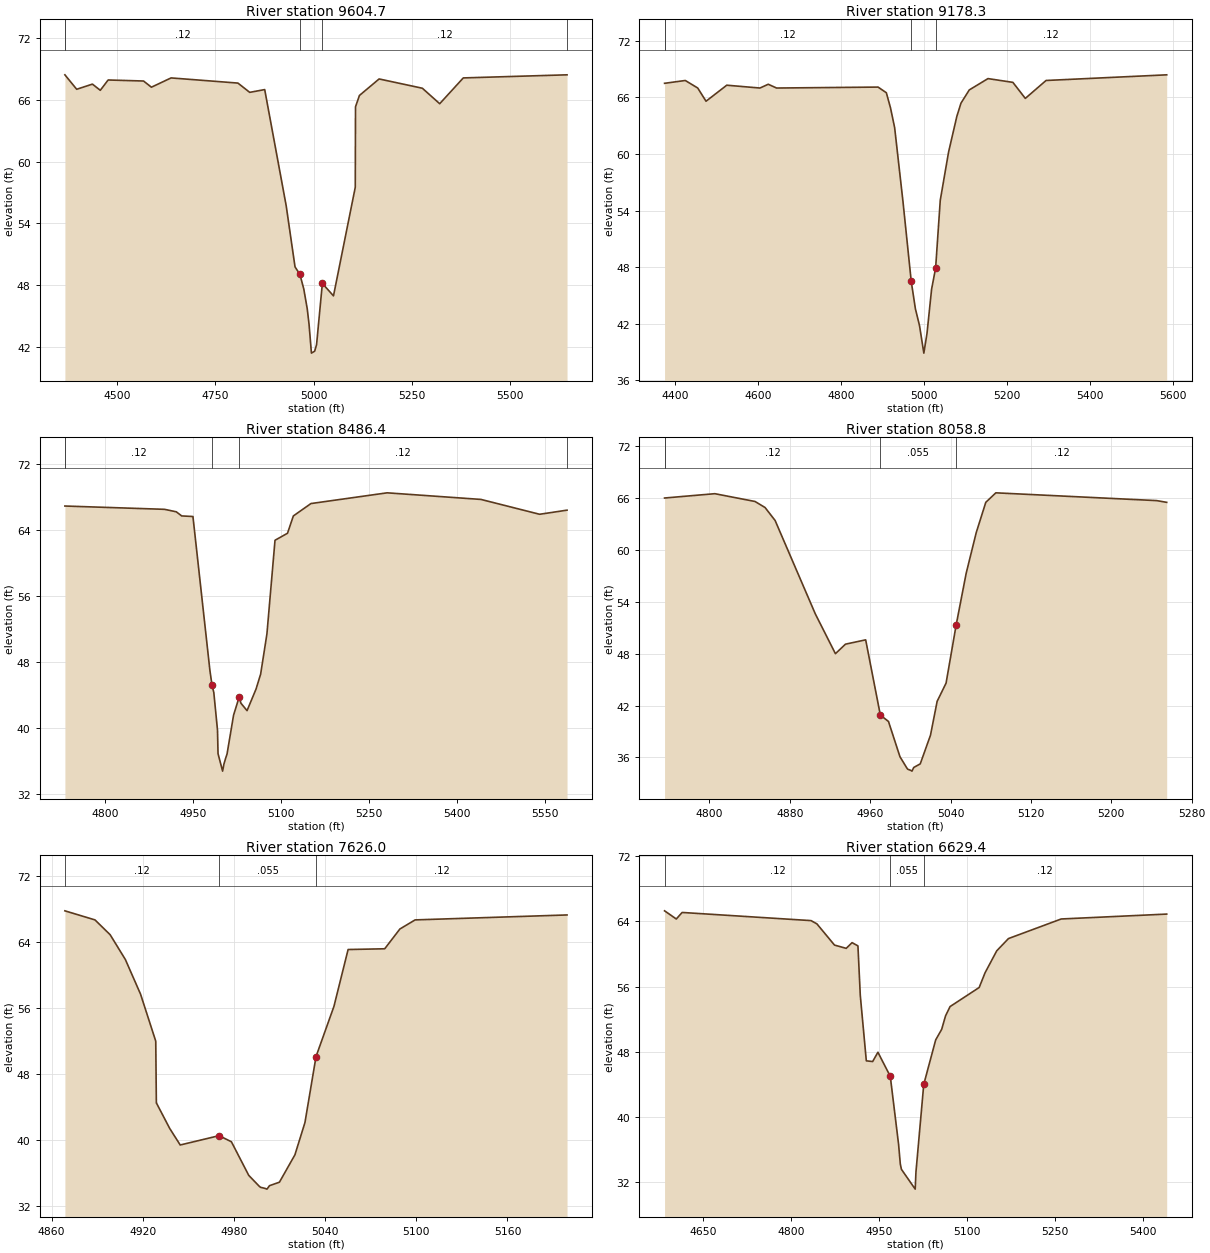
Type RM Length L Ch R = 1 ,9604.7  ,429.7,426.4,398.5
BEGIN DESCRIPTION:
Cross Section 9604.7
END DESCRIPTION:
XS GIS Cut Line= 5
      3081456.79     13852565.52      3080955.04     13852212.65
      3080900.47     13852160.36      3080716.29     13851985.27
      3080383.29     13851961.67
#Sta/Elev= 30
  4367.8    68.4  4397.8      67  4437.8    67.5  4457.8    66.9  4477.8    67.9
  4567.8    67.8  4587.8    67.2  4637.8    68.1  4807.8    67.6  4837.8    66.7
  4875.9   66.97  4930.5   55.72    4953   49.79  4965.5   49.05  4975.3   47.64
  4984.1   45.72  4988.8   44.17  4994.7   41.43    5003   41.62  5007.8   42.26
  5022.5   48.18  5050.8   46.98  5106.2    57.5  5106.8    65.3  5116.8    66.4
  5166.8      68  5276.8    67.1  5320.9    65.6  5380.9    68.1  5644.7    68.4
#Mann= 5 , 1 , 0
  4367.8      .2       0  4367.8     .12       0  4965.5    .055       0
  5022.5     .12       0  5644.7      .2       0
Bank Sta=4965.5,5022.5
Exp/Cntr=0.3,0.1

Type RM Length L Ch R = 1 ,9178.3  ,715.8,691.9,679.8
BEGIN DESCRIPTION:
Cross Section 9178.3-Interpolated
END DESCRIPTION:
XS GIS Cut Line= 4
      3081570.12     13851908.59      3081062.33     13851823.96
      3080848.26     13851754.27      3080390.26     13851644.74
#Sta/Elev= 30
  4374.9    67.5  4424.9    67.8  4454.9      67  4474.9    65.6  4524.9    67.3
  4604.9      67  4624.9    67.4  4644.9      67  4889.7    67.1  4909.7    66.5
  4919.7    64.9  4929.7    62.8  4949.7      55  4969.7    46.5  4979.7    43.6
  4989.7    41.8  5000.1   38.89  5007.7   40.97  5018.8   45.67  5028.5    47.9
  5039.7    55.1  5059.7    60.2  5079.7      64  5089.7    65.4  5109.7    66.8
  5154.8      68  5214.8    67.6  5244.8    65.9  5294.8    67.8  5585.7    68.4
#Mann= 4 , 1 , 0
  4374.9      .2       0  4374.9     .12       0  4969.7    .055       0
  5028.5     .12       0
Bank Sta=4969.7,5028.5
Exp/Cntr=0.3,0.1

Type RM Length L Ch R = 1 ,8486.4  ,368.6,427.6,449.7
BEGIN DESCRIPTION:
Cross Section 8486.4
END DESCRIPTION:
XS GIS Cut Line= 4
      3081712.23     13851409.99       3081523.5     13851346.32
      3081368.88     13851389.53      3080877.34     13851461.52
#Sta/Elev= 29
  4731.1    66.9  4901.1    66.5  4921.1    66.2  4930.3    65.7  4949.5   65.63
  4978.5   46.94  4981.9   45.25  4985.1    44.3  4991.4   39.74  4992.3   36.89
  5000.1   34.77  5002.3   35.61  5005.2   36.31  5007.7   36.85  5018.8   41.55
  5028.5   43.78  5031.3   43.01  5041.8    42.1  5057.1   44.71    5065   46.53
  5075.7    51.4  5089.5   62.75  5110.8    63.6  5120.8    65.7  5150.8    67.2
  5280.8    68.5  5440.8    67.7  5540.8    65.9  5587.6    66.4
#Mann= 5 , 1 , 0
  4731.1      .2       0  4731.1     .12       0  4981.9    .055       0
  5028.5     .12       0  5587.6      .2       0
Bank Sta=4981.9,5028.5
Exp/Cntr=0.3,0.1

Type RM Length L Ch R = 1 ,8058.8  ,358.8,432.8,484.3
BEGIN DESCRIPTION:
Cross Section 8058.8-Interpolated
END DESCRIPTION:
XS GIS Cut Line= 4
      3081525.32     13851027.43      3081326.18     13851007.52
       3081206.7     13851007.52      3081026.76     13851011.61
#Sta/Elev= 28
  4755.5      66  4805.5    66.5  4845.5    65.6  4855.5    64.9  4865.5    63.4
  4905.5    52.6  4925.5      48  4935.5    49.1  4955.6    49.6  4970.2    40.9
  4978.3   40.16  4989.7   36.09  4996.6   34.77  4997.5   34.64  5000.4   34.51
  5001.7   34.42  5003.4   34.84  5009.9   35.26  5020.1   38.58  5026.7   42.49
  5035.6    44.6  5045.6    51.3  5055.6    57.3  5065.6      62  5075.1    65.5
  5085.1    66.6  5245.1    65.7  5255.1    65.5
#Mann= 4 , 1 , 0
  4755.5      .2       0  4755.5     .12       0  4970.2    .055       0
  5045.6     .12       0
Bank Sta=4970.2,5045.6
Exp/Cntr=0.3,0.1

Type RM Length L Ch R = 1 ,7626.0  ,1025.2,996.6,931.5
BEGIN DESCRIPTION:
Cross Section 7626.0
END DESCRIPTION:
XS GIS Cut Line= 5
      3081432.27     13850768.93      3081425.23     13850750.45
      3081396.62     13850660.23      3081385.61     13850605.21
      3081320.31     13850459.18
#Sta/Elev= 28
  4868.7    67.8  4888.5    66.7  4898.5    64.9  4908.5    61.9  4918.5    57.7
  4928.5      52  4928.9   44.49    4929   44.49  4937.7   41.42  4944.6   39.42
  4970.2   40.55  4978.3   39.81  4989.7   35.74  4996.6   34.42  4997.5   34.29
  5000.4   34.16  5001.7   34.07  5003.4   34.49  5009.9   34.91  5020.1   38.23
  5026.7   42.14    5034   50.14  5045.8   56.23  5055.1   63.11  5079.2    63.2
  5089.2    65.6  5099.2    66.7  5199.2    67.3
#Mann= 3 , 1 , 0
  4868.7     .12       0  4970.2    .055       0    5034     .12       0
Bank Sta=4970.2,5034
Exp/Cntr=0.3,0.1

Type RM Length L Ch R = 1 ,6629.4  ,906.6,865.1,818.6
BEGIN DESCRIPTION:
Cross Section 6629.4
END DESCRIPTION:
XS GIS Cut Line= 4
      3082400.52     13850512.89      3082180.05     13850176.08
      3082158.04     13850149.68       3081904.8     13849814.64
#Sta/Elev= 30
  4583.7    65.3  4603.7    64.3  4613.7    65.1  4833.7    64.1  4843.7    63.7
  4873.7    61.1  4893.7    60.7  4903.7    61.4  4913.7      61  4917.7   54.94
    4928   46.91  4938.8   46.82  4947.8   47.96  4968.9   45.01  4983.1   36.65
    4986   34.26  4987.9   33.61  5011.4   31.18  5012.7   33.27    5026   44.01
  5046.4   49.48  5056.6   50.77  5063.2   52.42  5070.9   53.56  5120.6    55.9
  5130.6    57.7  5150.6    60.4  5170.6    61.9  5260.6    64.3  5440.6    64.9
#Mann= 3 , 1 , 0
  4583.7     .12       0  4968.9    .055       0    5026     .12       0
Bank Sta=4968.9,5026
Exp/Cntr=0.3,0.1

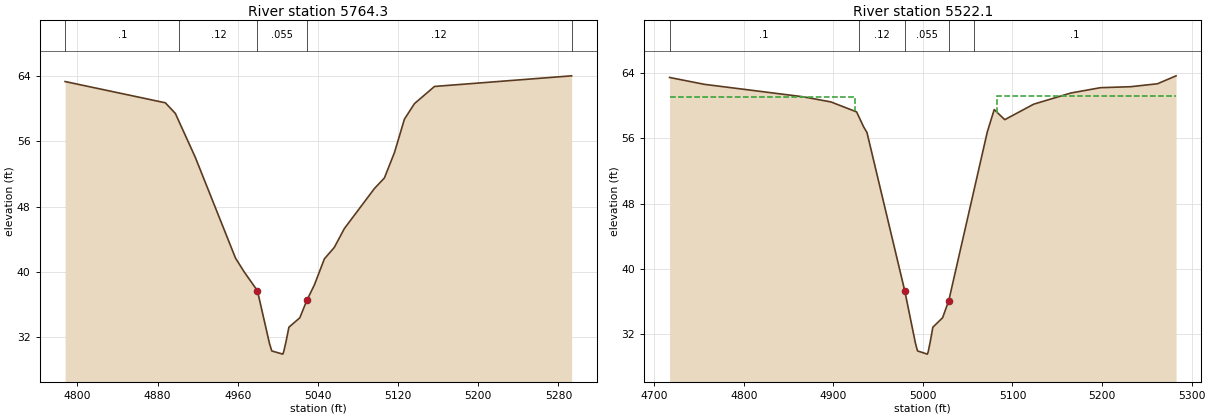
Type RM Length L Ch R = 1 ,5764.3  ,231.5,242.2,205.8
BEGIN DESCRIPTION:
Cross Section 5764.3-Interpolated
END DESCRIPTION:
XS GIS Cut Line= 4
      3083002.98     13849729.11       3082839.1     13849657.78
      3082758.17     13849618.71      3082523.73     13849585.21
#Sta/Elev= 27
  4787.8    63.3  4887.8    60.7  4897.8    59.4  4901.9   58.29  4917.8      54
  4957.8    41.7  4966.5      40  4979.7    37.7  4991.8   31.21    4994   30.33
    5005   29.94  5005.9   30.22  5008.2   31.45  5011.1   33.23    5022   34.39
    5029   36.52  5036.5    38.4  5046.5    41.6  5056.4      43  5066.4    45.3
  5096.4    50.2  5106.4    51.5  5116.4    54.6  5126.4    58.7  5136.4    60.6
  5156.4    62.7  5293.2      64
#Mann= 5 , 1 , 0
  4787.8      .1       0  4901.9     .12       0  4979.7    .055       0
    5029     .12       0  5293.2      .2       0
Bank Sta=4979.7,5029
Exp/Cntr=0.5,0.3

Type RM Length L Ch R = 1 ,5522.1  ,36.8,36.8,36.8
BEGIN DESCRIPTION:
Upstream Section of Bridge/Culvert/Weir
END DESCRIPTION:
XS GIS Cut Line= 4
      3083164.89     13849433.83      3082900.18      13849430.5
      3082850.94     13849429.33      3082599.53     13849429.78
#Sta/Elev= 27
  4717.2   63.41  4756.1   62.57  4866.2   61.05  4897.3   60.42    4926    59.2
  4928.4   58.64  4933.9   57.36  4937.6   56.67  4979.7   37.35  4991.7   30.91
    4994   29.98    5005   29.59  5005.9   29.87  5008.2    31.1  5011.1   32.88
    5022   34.04  5028.9   36.14  5057.1   49.66  5071.9   56.76  5079.6   59.48
  5091.4   58.25  5123.8   60.15  5165.2   61.51  5198.2   62.16  5231.9   62.28
  5261.9   62.64  5282.6   63.61
#Mann= 5 , 1 , 0
  4717.2      .1       0  4928.4     .12       0  4979.7    .055       0
  5028.9     .12       0  5057.1      .1       0
#XS Ineff= 2 , 0
       0    4924      61    5083       0    61.2
Permanent Ineff=
       F       F
Bank Sta=4979.7,5028.9
Exp/Cntr=0.5,0.3