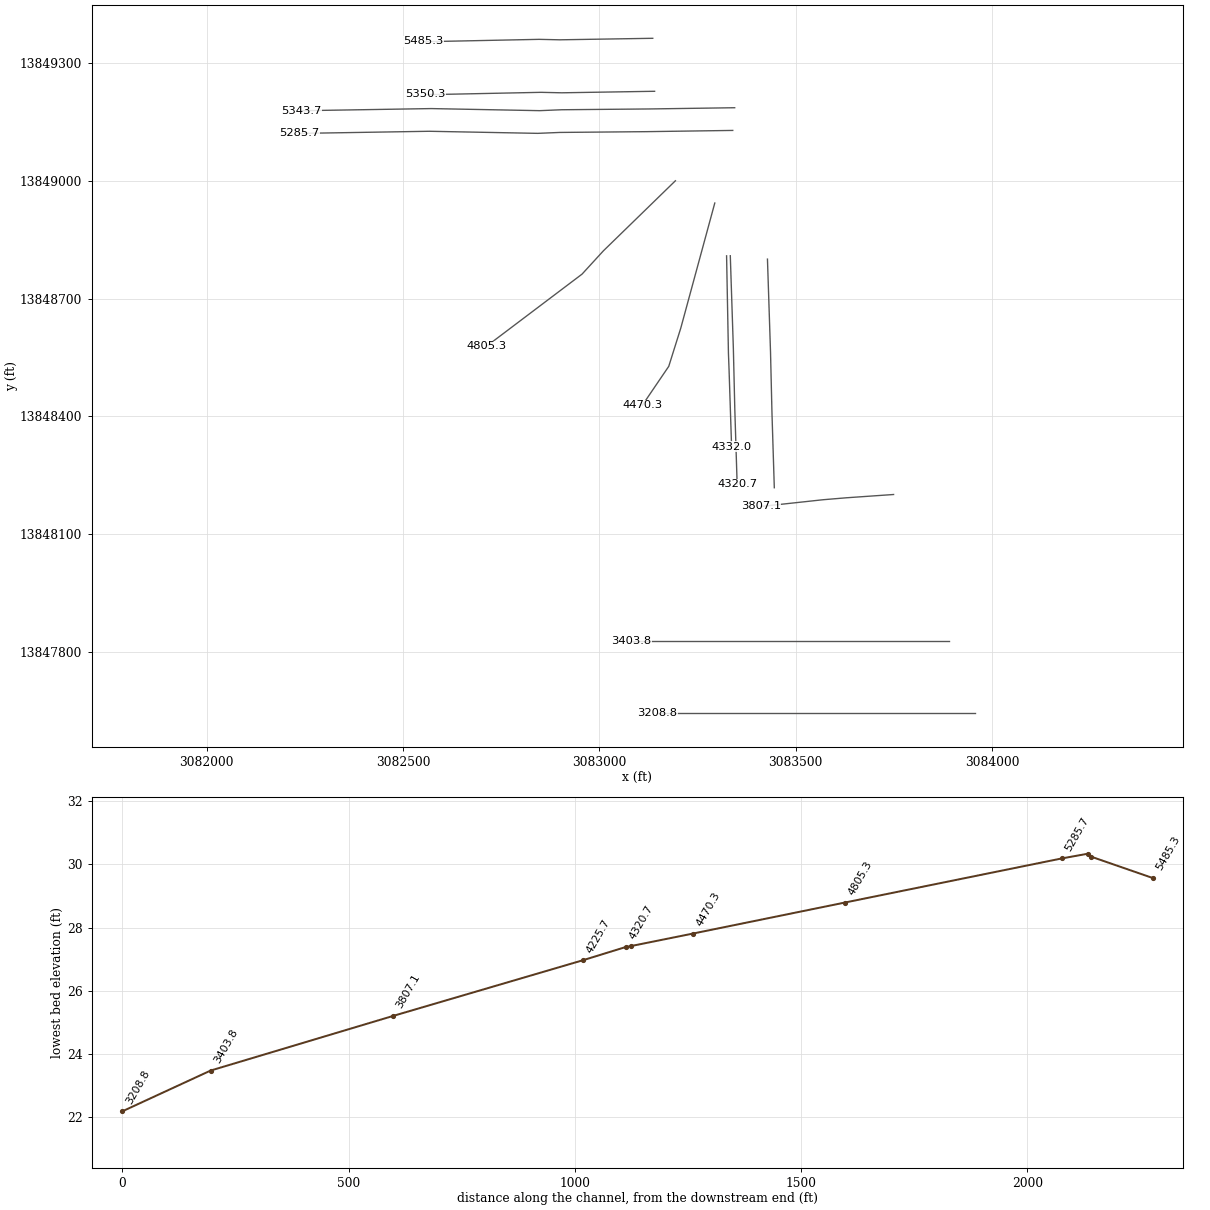
HEC-RAS study W140-00-00.PRJ: W140-00-00

--- W140-00-00.g01 (geometry) --- (continued)

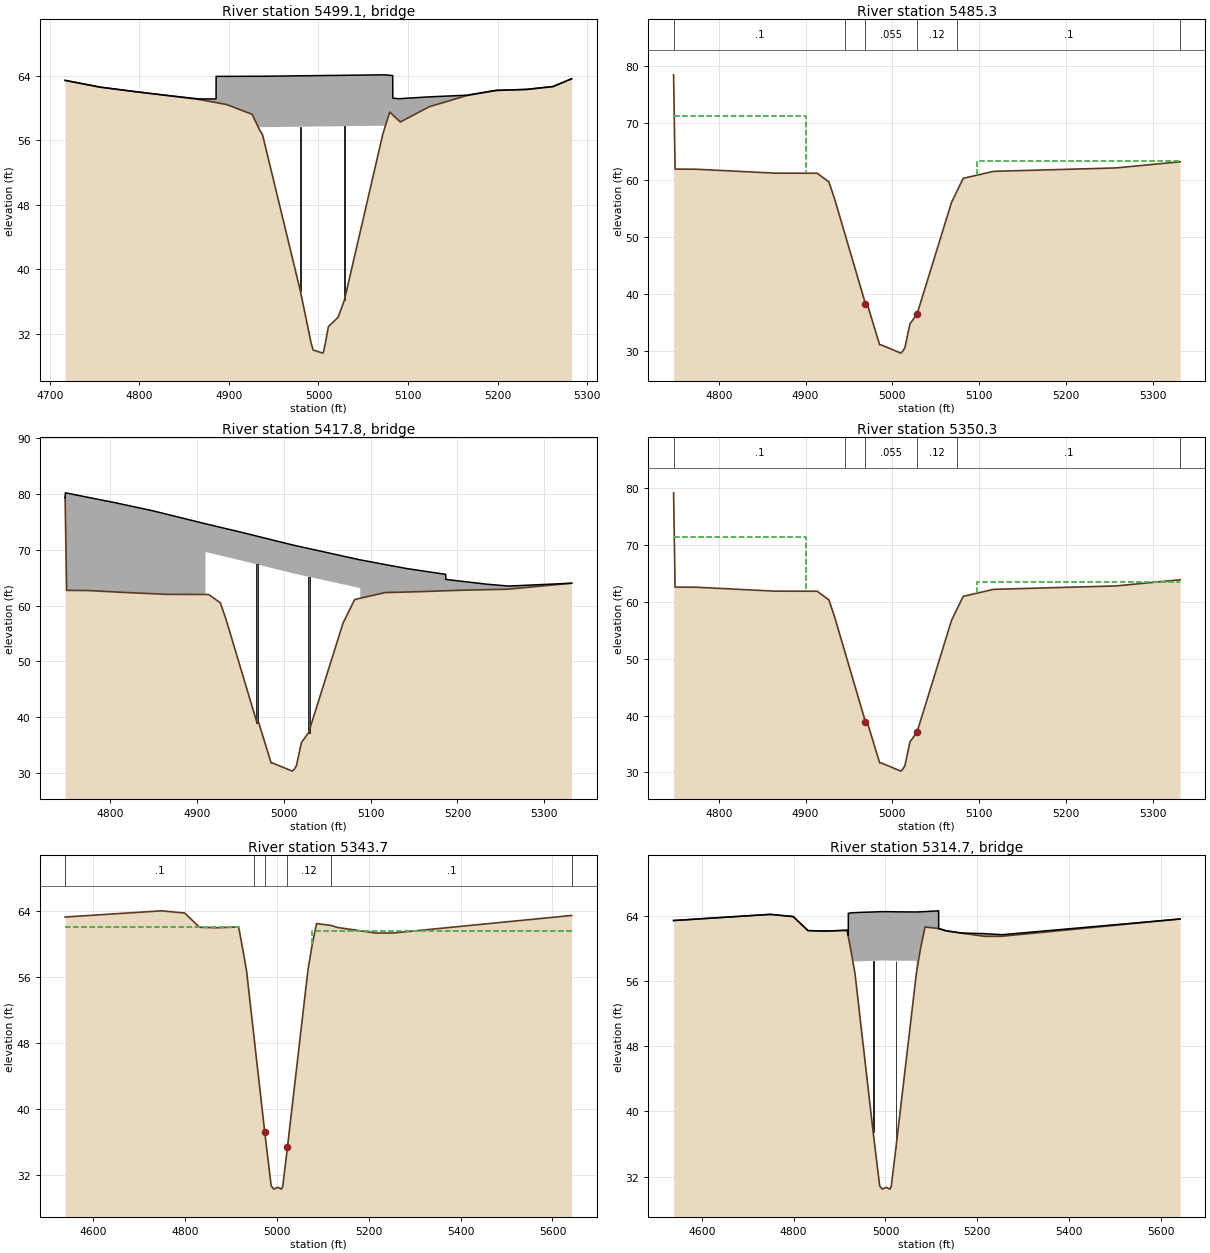
Type RM Length L Ch R = 3 ,5499.1  ,,,
BEGIN DESCRIPTION:
INTERSTATE 10 and US ROUTE 90
Structure ID: W40-11
END DESCRIPTION:
Bridge Culvert--1,0,-1,-1, 0
Deck Dist Width WeirC Skew NumUp NumDn MinLoCord MaxHiCord MaxSubmerge Is_Ogee
10,26,2.6,0, 53, 53, , , 0.95, 0, 1,1,,
  4717.2  4754.7  4756.1  4790.4  4794.4  4829.3  4829.8  4866.2  4871.3 4885.69
  4885.8 4885.91  4897.3    4926  4928.4  4933.9    4934 4934.11  4934.2  4937.6
  4979.7  4991.7  4991.8    4994    5005  5005.9  5008.2  5011.1    5022  5028.9
    5029  5057.1  5071.9 5073.49  5073.6  5073.7  5079.6 5082.79  5082.9 5083.01
  5089.2  5091.4  5123.8    5126  5163.3  5165.2  5198.2  5200.5    5231  5231.9
  5261.9  5263.6  5282.6
    63.4    62.6   62.57   62.08   62.02   61.56   61.55   61.11    61.1    61.1
    63.9    63.9    63.9   63.91   63.91   63.91   63.91   63.91   63.91   63.91
   63.97   63.98   63.98   63.99      64      64   64.01   64.01   64.02   64.03
   64.03   64.07   64.09   64.09   64.09   64.09   64.03      64      64    61.2
   61.13   61.14   61.36   61.37   61.55   61.56   62.16   62.17   62.28   62.28
   62.64   62.72    63.6
    63.4   62.59   62.56   62.07   62.01   61.55   61.54   61.04   60.94   60.65
   60.64   60.64   60.41   59.19   58.63   57.35   57.33   57.31    57.6    57.6
   57.66   57.67   57.67   57.68   57.69   57.69    57.7    57.7   57.71   57.72
   57.72   57.76   57.78   57.78   57.35   57.39   59.47   59.14   59.13   59.11
   58.47   58.24   60.14   60.21   61.44    61.5   62.15   62.16   62.27   62.27
   62.63   62.71    63.6
  4717.2  4754.7  4756.1  4790.4  4794.4  4829.3  4829.8  4866.2  4871.3 4885.69
  4885.8 4885.91  4897.3    4926  4928.4  4933.9    4934 4934.11  4934.2  4937.6
  4979.7  4991.7  4991.8    4994    5005  5005.9  5008.2  5011.1    5022  5028.9
    5029  5057.1  5071.9 5073.49  5073.6  5073.7  5079.6 5082.79  5082.9 5083.01
  5089.2  5091.4  5123.8    5126  5163.3  5165.2  5198.2  5200.5    5231  5231.9
  5261.9  5263.6  5282.6
    63.4    62.6   62.57   62.08   62.02   61.56   61.55   61.11    61.1    61.1
    63.9    63.9    63.9   63.91   63.91   63.91   63.91   63.91   63.91   63.91
   63.97   63.98   63.98   63.99      64      64   64.01   64.01   64.02   64.03
   64.03   64.07   64.09   64.09   64.09   64.09   64.03      64      64    61.2
   61.13   61.14   61.36   61.37   61.55   61.56   62.16   62.17   62.28   62.28
   62.64   62.72    63.6
   63.32   62.51   62.48   61.99   61.93   61.47   61.46   60.96   60.86   60.57
   60.56   60.56   60.33   59.11   58.55   57.27   57.25   57.23   57.52   57.52
   57.58   57.59   57.59    57.6   57.61   57.61   57.62   57.62   57.63   57.64
   57.64   57.68    57.7    57.7   57.27   57.31   59.39   59.06   59.05   59.03
   58.39   58.16   60.06   60.13   61.36   61.42   62.07   62.08   62.19   62.19
   62.55   62.63   63.52
Pier Skew, UpSta & Num, DnSta & Num=  ,4979.7, 2 ,4979.7, 2 , 0 , 0 , 0 ,,
     1.5     1.5
   35.94   58.66
     1.5     1.5
   35.86   58.58
Pier Skew, UpSta & Num, DnSta & Num=  ,5029, 2 ,5029, 2 , 0 , 0 , 0 ,,
     1.5     1.5
   34.93   58.72
     1.5     1.5
   34.85   58.64
Abutment Skew #Up #Dn= , 2 , 2
    4934  4991.8
    57.6   30.85
    4934  4991.8
   57.52   30.77
Abutment Skew #Up #Dn= , 2 , 2
    5029 5073.69
   36.16   57.78
    5029 5073.69
   36.08    57.7
BR Coef= 1 , 1 , 0 ,1.25, 0 ,,,0.8,0,2,0,
WSPro=,,,, 1 ,,,, 0 ,,,, 0 ,,,,-1 ,-1 ,-1 , 0 , 0 , 0 , 0 , 0
BR U #Sta/Elev= 53
  4717.2    63.4  4754.7   62.59  4756.1   62.56  4790.4   62.07  4794.4   62.01
  4829.3   61.55  4829.8   61.54  4866.2   61.04  4871.3   60.94 4885.69   60.65
  4885.8   60.64 4885.91   60.64  4897.3   60.41    4926   59.19  4928.4   58.63
  4933.9   57.35    4934   57.33 4934.11   57.31  4934.2   57.29  4937.6   56.66
  4979.7   37.34  4991.7    30.9  4991.8   30.85    4994   29.97    5005   29.58
  5005.9   29.86  5008.2   31.09  5011.1   32.87    5022   34.03  5028.9   36.13
    5029   36.16  5057.1   49.65  5071.9   56.75 5073.49   57.31  5073.6   57.35
  5073.7   57.39  5079.6   59.47 5082.79   59.14  5082.9   59.13 5083.01   59.11
  5089.2   58.47  5091.4   58.24  5123.8   60.14    5126   60.21  5163.3   61.44
  5165.2    61.5  5198.2   62.15  5200.5   62.16    5231   62.27  5231.9   62.27
  5261.9   62.63  5263.6   62.71  5282.6    63.6
BR U #Mann= 5
  4717.2      .1  4928.4     .12  4979.7    .055  5028.9     .12  5057.1      .1
BR U Banks=4979.7,5028.9
BR D #Sta/Elev= 53
  4717.2   63.32  4754.7   62.51  4756.1   62.48  4790.4   61.99  4794.4   61.93
  4829.3   61.47  4829.8   61.46  4866.2   60.96  4871.3   60.86 4885.69   60.57
  4885.8   60.56 4885.91   60.56  4897.3   60.33    4926   59.11  4928.4   58.55
  4933.9   57.27    4934   57.25 4934.11   57.23  4934.2   57.21  4937.6   56.58
  4979.7   37.26  4991.7   30.82  4991.8   30.77    4994   29.89    5005    29.5
  5005.9   29.78  5008.2   31.01  5011.1   32.79    5022   33.95  5028.9   36.05
    5029   36.08  5057.1   49.57  5071.9   56.67 5073.49   57.23  5073.6   57.27
  5073.7   57.31  5079.6   59.39 5082.79   59.06  5082.9   59.05 5083.01   59.03
  5089.2   58.39  5091.4   58.16  5123.8   60.06    5126   60.13  5163.3   61.36
  5165.2   61.42  5198.2   62.07  5200.5   62.08    5231   62.19  5231.9   62.19
  5261.9   62.55  5263.6   62.63  5282.6   63.52
BR D #Mann= 5
  4717.2      .1  4928.4     .12  4979.7    .055  5028.9     .12  5057.1      .1
BR D Banks=4979.7,5028.9
BC Design=,, 0 ,, 0 ,,,,,,
BC HTab HWMax=63.61

Type RM Length L Ch R = 1 ,5485.3  ,135,135,135
BEGIN DESCRIPTION:
Upstream Section of Bridge/Culvert/Weir
END DESCRIPTION:
XS GIS Cut Line= 6
      3083136.06     13849362.71      3083123.15     13849362.55
      3082899.46      13849358.9      3082846.71     13849360.08
      3082582.31      13849354.6      3082552.56      13849354.6
#Sta/Elev= 23
    4748   78.47  4749.7   61.91  4774.5   61.88  4865.2   61.19  4913.4   61.18
  4926.9   59.67  4933.4   56.73  4945.5   50.46  4969.1   38.22  4970.9   38.31
  4985.5      31  4986.9   31.03  5009.9   29.57  5012.2   29.95  5014.5   30.52
  5020.3   34.69  5028.6   36.47  5068.2   56.04  5074.4   57.99  5081.7   60.28
  5116.7   61.51  5257.6   62.11  5331.6   63.19
#Mann= 6 , 1 , 0
    4748      .1       0  4945.5     .12       0  4969.1    .055       0
  5028.6     .12       0  5074.4      .1       0  5331.6      .2       0
#XS Ineff= 2 , 0
       0    4900    71.3    5098       0    63.4
Permanent Ineff=
       F       F
Bank Sta=4969.1,5028.6
Exp/Cntr=0.5,0.3

Type RM Length L Ch R = 3 ,5417.8  ,,,
BEGIN DESCRIPTION:
INTERSTATE 10 and US ROUTE 90
Structure ID: W40-10
END DESCRIPTION:
Bridge Culvert--1,0,-1,-1, 0
Deck Dist Width WeirC Skew NumUp NumDn MinLoCord MaxHiCord MaxSubmerge Is_Ogee
10,115,2.6,0, 49, 49, , , 0.95, 0, 1,1,,
    4748 4748.09  4748.2 4748.31  4749.7  4774.5  4804.7  4817.1  4848.9  4865.2
  4909.6 4909.71  4909.8  4913.4  4926.9  4933.4  4945.5    4949  4969.1  4970.8
  4970.9  4985.5  4986.9  5009.9  5010.2  5012.2  5014.5  5020.3  5020.4  5028.6
  5068.2  5074.4  5081.7 5088.09  5088.2  5088.3  5116.7  5141.4  5161.6 5186.39
  5186.5 5186.61  5189.1  5208.6  5233.5  5257.6  5258.9  5259.1  5331.6
   79.28   79.27   80.17   80.17   80.13   79.36   78.43   78.02   76.96   76.34
   74.64   74.64   74.63    74.5      74   73.76   73.32   73.19   72.42   72.35
   72.35   71.79   71.73   70.85   70.84   70.77   70.69   70.49   70.49   70.21
   68.85   68.64   68.39   68.17   68.17   68.17   67.34   66.63   66.16   65.59
   65.59   64.69   64.63   64.28   63.83   63.51   63.49   63.49      64
   79.28    78.4   77.33   76.26   62.72   62.69   62.44   62.34   62.12      62
   61.99   61.99   69.58   69.45   68.95   68.71   68.27   68.14   67.37    67.3
    67.3   66.74   66.68    65.8   65.79   65.72   65.64   65.44   65.44   65.16
    63.8   63.59   63.34   63.12   61.32   61.32   62.32   62.42   62.51   62.64
   62.64   62.64   62.66   62.76   62.84   62.92   62.94   62.94      64
    4748 4748.09  4748.2 4748.31  4749.7  4774.5  4804.7  4817.1  4848.9  4865.2
  4909.6 4909.71  4909.8  4913.4  4926.9  4933.4  4945.5    4949  4969.1  4970.8
  4970.9  4985.5  4986.9  5009.9  5010.2  5012.2  5014.5  5020.3  5020.4  5028.6
  5068.2  5074.4  5081.7 5088.09  5088.2  5088.3  5116.7  5141.4  5161.6 5186.39
  5186.5 5186.61  5189.1  5208.6  5233.5  5257.6  5258.9  5259.1  5331.6
   79.28   79.27   80.17   80.17   80.13   79.36   78.43   78.02   76.96   76.34
   74.64   74.64   74.63    74.5      74   73.76   73.32   73.19   72.42   72.35
   72.35   71.79   71.73   70.85   70.84   70.77   70.69   70.49   70.49   70.21
   68.85   68.64   68.39   68.17   68.17   68.17   67.34   66.63   66.16   65.59
   65.59   64.69   64.63   64.28   63.83   63.51   63.49   63.49      64
      79   78.12   77.05   75.98   62.44   62.41   62.16   62.06   61.84   61.72
   61.71   61.71    69.3   69.17   68.67   68.43   67.99   67.86   67.09   67.02
   67.02   66.46    66.4   65.52   65.51   65.44   65.36   65.16   65.16   64.88
   63.52   63.31   63.06   62.84   61.04   61.04   62.04   62.14   62.23   62.36
   62.36   62.36   62.38   62.48   62.56   62.64   62.66   62.66   63.72
Pier Skew, UpSta & Num, DnSta & Num=  ,4969.1, 2 ,4969.1, 2 , 0 , 0 , 0 ,,
       2       2
   38.08   68.41
       2       2
    37.8   68.13
Pier Skew, UpSta & Num, DnSta & Num=  ,5028.6, 2 ,5028.6, 2 , 0 , 0 , 0 ,,
       2       2
   36.07   66.19
       2       2
   35.79   65.91
Abutment Skew #Up #Dn= , 2 , 2
  4909.6  4970.9
   69.58   39.12
  4909.6  4970.9
    69.3   38.84
Abutment Skew #Up #Dn= , 2 , 2
  5020.4 5088.29
   35.52   63.12
  5020.4 5088.29
   35.24   62.84
BR Coef= 1 , 1 , 0 ,1.25, 0 ,,,0.8,0,2,0,
WSPro=,,,, 1 ,,,, 0 ,,,, 0 ,,,,-1 ,-1 ,-1 , 0 , 0 , 0 , 0 , 0
BR U #Sta/Elev= 49
    4748   79.28 4748.09    78.4  4748.2   77.33 4748.31   76.26  4749.7   62.72
  4774.5   62.69  4804.7   62.44  4817.1   62.34  4848.9   62.12  4865.2      62
  4909.6   61.99 4909.71   61.99  4909.8   61.99  4913.4   61.99  4926.9   60.48
  4933.4   57.54  4945.5   51.27    4949   49.45  4969.1   39.03  4970.8   39.11
  4970.9   39.12  4985.5   31.81  4986.9   31.84  5009.9   30.38  5010.2   30.43
  5012.2   30.76  5014.5   31.33  5020.3    35.5  5020.4   35.52  5028.6   37.28
  5068.2   56.85  5074.4    58.8  5081.7   61.09 5088.09   61.31  5088.2   61.32
  5088.3   61.32  5116.7   62.32  5141.4   62.42  5161.6   62.51 5186.39   62.64
  5186.5   62.64 5186.61   62.64  5189.1   62.66  5208.6   62.76  5233.5   62.84
  5257.6   62.92  5258.9   62.94  5259.1   62.94  5331.6      64
BR U #Mann= 6
    4748      .1  4945.5     .12  4969.1    .055  5028.6     .12  5074.4      .1
  5331.6      .2
BR U Banks=4969.1,5028.6
BR D #Sta/Elev= 49
    4748      79 4748.09   78.12  4748.2   77.05 4748.31   75.98  4749.7   62.44
  4774.5   62.41  4804.7   62.16  4817.1   62.06  4848.9   61.84  4865.2   61.72
  4909.6   61.71 4909.71   61.71  4909.8   61.71  4913.4   61.71  4926.9    60.2
  4933.4   57.26  4945.5   50.99    4949   49.17  4969.1   38.75  4970.8   38.83
  4970.9   38.84  4985.5   31.53  4986.9   31.56  5009.9    30.1  5010.2   30.15
  5012.2   30.48  5014.5   31.05  5020.3   35.22  5020.4   35.24  5028.6      37
  5068.2   56.57  5074.4   58.52  5081.7   60.81 5088.09   61.03  5088.2   61.04
  5088.3   61.04  5116.7   62.04  5141.4   62.14  5161.6   62.23 5186.39   62.36
  5186.5   62.36 5186.61   62.36  5189.1   62.38  5208.6   62.48  5233.5   62.56
  5257.6   62.64  5258.9   62.66  5259.1   62.66  5331.6   63.72
BR D #Mann= 6
    4748      .1  4945.5     .12  4969.1    .055  5028.6     .12  5074.4      .1
  5331.6      .2
BR D Banks=4969.1,5028.6
BC Design=,, 0 ,, 0 ,,,,,,
BC HTab HWMax=78.47

Type RM Length L Ch R = 1 ,5350.3  ,6.6,6.6,6.6
BEGIN DESCRIPTION:
Downstream Section of Bridge/Culvert/Weir
END DESCRIPTION:
XS GIS Cut Line= 6
      3083140.79     13849227.79      3083127.89     13849227.63
       3082904.2     13849223.98      3082851.45     13849225.16
      3082587.05     13849219.68      3082557.29     13849219.68
#Sta/Elev= 23
    4748   79.14  4749.7   62.58  4774.5   62.55  4865.2   61.86  4913.4   61.85
  4926.9   60.34  4933.4    57.4  4945.5   51.13  4969.1   38.89  4970.9   38.98
  4985.5   31.67  4986.9    31.7  5009.9   30.24  5012.2   30.62  5014.5   31.19
  5020.3   35.36  5028.6   37.14  5068.2   56.71  5074.4   58.66  5081.7   60.95
  5116.7   62.18  5257.6   62.78  5331.6   63.86
#Mann= 6 , 1 , 0
    4748      .1       0  4945.5     .12       0  4969.1    .055       0
  5028.6     .12       0  5074.4      .1       0  5331.6      .2       0
#XS Ineff= 2 , 0
       0    4900    71.3    5098       0    63.4
Permanent Ineff=
       F       F
Bank Sta=4969.1,5028.6
Exp/Cntr=0.5,0.3

Type RM Length L Ch R = 1 ,5343.7  ,58,58,58
BEGIN DESCRIPTION:
Upstream Section of Bridge/Culvert/Weir
END DESCRIPTION:
XS GIS Cut Line= 6
      3083344.69     13849185.96      3083125.92     13849182.82
       3082904.3     13849180.82      3082848.03     13849178.48
      3082571.88     13849183.79      3082241.66     13849178.35
#Sta/Elev= 24
  4538.5   63.26  4748.4   64.01    4799   63.74  4831.3   62.02    4868   61.96
  4916.5   62.06  4926.8   58.94  4933.7   56.74  4950.9   48.27  4973.2    37.3
  4987.4   30.72  4993.1   30.35  5001.9   30.56  5009.8   30.34  5012.6   30.69
  5022.8   35.42  5067.4   56.83  5076.5   59.87  5086.2   62.47  5117.9   62.24
  5132.2   61.99  5215.8   61.32  5253.7   61.33  5641.7   63.45
#Mann= 7 , 1 , 0
  4538.5      .2       0  4538.5      .1       0  4950.9     .12       0
  4973.2    .055       0  5022.8     .12       0  5117.9      .1       0
  5641.7      .2       0
#XS Ineff= 2 , 0
       0    4918    62.1    5077       0    61.6
Permanent Ineff=
       F       F
Bank Sta=4973.2,5022.8
Exp/Cntr=0.5,0.3

Type RM Length L Ch R = 3 ,5314.7  ,,,
BEGIN DESCRIPTION:
INTERSTATE 10 and US ROUTE 90
Structure ID: W40-9
END DESCRIPTION:
Bridge Culvert--1,0,-1,-1, 0
Deck Dist Width WeirC Skew NumUp NumDn MinLoCord MaxHiCord MaxSubmerge Is_Ogee
10,38,2.6,0, 51, 51, , , 0.95, 0, 1,1,,
  4538.5  4747.6  4748.4    4799  4799.4  4831.3  4849.3    4868    4888  4916.5
  4918.9 4918.99  4919.1 4919.21  4926.8  4928.1 4928.21  4928.3  4928.4  4933.7
  4950.9  4973.2  4987.4  4993.1  4993.9  5001.9  5009.8  5012.6  5022.8  5067.4
  5067.7 5067.79  5067.9    5068  5076.5  5086.2  5087.4  5115.6 5115.69  5115.8
 5115.91  5117.9  5131.6  5132.2  5166.2  5168.9  5213.6  5215.8  5253.7  5255.1
  5641.7
    63.4   64.15   64.16   63.89   63.87   62.17   62.14   62.11   62.15   62.21
   61.59   61.59   64.29   64.29   64.35   64.36   64.36   64.36   64.36   64.37
   64.41   64.45   64.48   64.49   64.49   64.49   64.48   64.48   64.47   64.45
   64.45   64.45   64.45   64.45   64.47    64.5    64.5   64.59   64.59   64.59
   62.42   62.39   62.15   62.14   61.87   61.86    61.8   61.79   61.67   61.67
   63.59
    63.4   64.15   64.15   63.88   63.86   62.16   62.13    62.1   62.14    62.2
   61.47   61.45   61.41   61.38   59.08   58.67   58.63    58.6   58.57   58.38
   58.42   58.46   58.49    58.5    58.5    58.5   58.49   58.49   58.48   58.46
   58.46   58.46   57.14   57.17   60.01   62.61    62.6   62.42   62.42   62.42
   62.41   62.38   62.14   62.13   61.85   61.83   61.48   61.46   61.47   61.48
   63.59
  4538.5  4747.6  4748.4    4799  4799.4  4831.3  4849.3    4868    4888  4916.5
  4918.9 4918.99  4919.1 4919.21  4926.8  4928.1 4928.21  4928.3  4928.4  4933.7
  4950.9  4973.2  4987.4  4993.1  4993.9  5001.9  5009.8  5012.6  5022.8  5067.4
  5067.7 5067.79  5067.9    5068  5076.5  5086.2  5087.4  5115.6 5115.69  5115.8
 5115.91  5117.9  5131.6  5132.2  5166.2  5168.9  5213.6  5215.8  5253.7  5255.1
  5641.7
    63.4   64.15   64.16   63.89   63.87   62.17   62.14   62.11   62.15   62.21
   61.59   61.59   64.29   64.29   64.35   64.36   64.36   64.36   64.36   64.37
   64.41   64.45   64.48   64.49   64.49   64.49   64.48   64.48   64.47   64.45
   64.45   64.45   64.45   64.45   64.47    64.5    64.5   64.59   64.59   64.59
   62.42   62.39   62.15   62.14   61.87   61.86    61.8   61.79   61.67   61.67
   63.59
   63.14   63.89   63.89   63.62    63.6    61.9   61.87   61.84   61.88   61.94
   61.21   61.19   61.15   61.12   58.82   58.41   58.37   58.34   58.31   58.12
   58.16    58.2   58.23   58.24   58.24   58.24   58.23   58.23   58.22    58.2
    58.2    58.2   56.88   56.91   59.75   62.35   62.34   62.16   62.16   62.16
   62.15   62.12   61.88   61.87   61.59   61.57   61.22    61.2   61.21   61.22
   63.33
Pier Skew, UpSta & Num, DnSta & Num=  ,4973.2, 2 ,4973.2, 2 , 0 , 0 , 0 ,,
     1.5     1.5
   36.09   59.46
     1.5     1.5
   35.83    59.2
Pier Skew, UpSta & Num, DnSta & Num=  ,5022.8, 2 ,5022.8, 2 , 0 , 0 , 0 ,,
     1.5     1.5
   34.21   59.48
     1.5     1.5
   33.95   59.22
BR Coef= 1 , 1 , 0 ,1.25, 0 ,,,0.8,0,2,0,
WSPro=,,,, 1 ,,,, 0 ,,,, 0 ,,,,-1 ,-1 ,-1 , 0 , 0 , 0 , 0 , 0
BR U #Sta/Elev= 51
  4538.5    63.4  4747.6   64.15  4748.4   64.15    4799   63.88  4799.4   63.86
  4831.3   62.16  4849.3   62.13    4868    62.1    4888   62.14  4916.5    62.2
  4918.9   61.47 4918.99   61.45  4919.1   61.41 4919.21   61.38  4926.8   59.08
  4928.1   58.67 4928.21   58.63  4928.3    58.6  4928.4   58.57  4933.7   56.88
  4950.9   48.41  4973.2   37.44  4987.4   30.86  4993.1   30.49  4993.9   30.51
  5001.9    30.7  5009.8   30.48  5012.6   30.83  5022.8   35.56  5067.4   56.97
  5067.7   57.07 5067.79    57.1  5067.9   57.14    5068   57.17  5076.5   60.01
  5086.2   62.61  5087.4    62.6  5115.6   62.42 5115.69   62.42  5115.8   62.42
 5115.91   62.41  5117.9   62.38  5131.6   62.14  5132.2   62.13  5166.2   61.85
  5168.9   61.83  5213.6   61.48  5215.8   61.46  5253.7   61.47  5255.1   61.48
  5641.7   63.59
BR U #Mann= 7
  4538.5      .2  4538.5      .1  4950.9     .12  4973.2    .055  5022.8     .12
  5117.9      .1  5641.7      .2
BR U Banks=4973.2,5022.8
BR D #Sta/Elev= 51
  4538.5   63.14  4747.6   63.89  4748.4   63.89    4799   63.62  4799.4    63.6
  4831.3    61.9  4849.3   61.87    4868   61.84    4888   61.88  4916.5   61.94
  4918.9   61.21 4918.99   61.19  4919.1   61.15 4919.21   61.12  4926.8   58.82
  4928.1   58.41 4928.21   58.37  4928.3   58.34  4928.4   58.31  4933.7   56.62
  4950.9   48.15  4973.2   37.18  4987.4    30.6  4993.1   30.23  4993.9   30.25
  5001.9   30.44  5009.8   30.22  5012.6   30.57  5022.8    35.3  5067.4   56.71
  5067.7   56.81 5067.79   56.84  5067.9   56.88    5068   56.91  5076.5   59.75
  5086.2   62.35  5087.4   62.34  5115.6   62.16 5115.69   62.16  5115.8   62.16
 5115.91   62.15  5117.9   62.12  5131.6   61.88  5132.2   61.87  5166.2   61.59
  5168.9   61.57  5213.6   61.22  5215.8    61.2  5253.7   61.21  5255.1   61.22
  5641.7   63.33
BR D #Mann= 7
  4538.5      .2  4538.5      .1  4950.9     .12  4973.2    .055  5022.8     .12
  5117.9      .1  5641.7      .2
BR D Banks=4973.2,5022.8
BC Design=,, 0 ,, 0 ,,,,,,
BC HTab HWMax=64.01

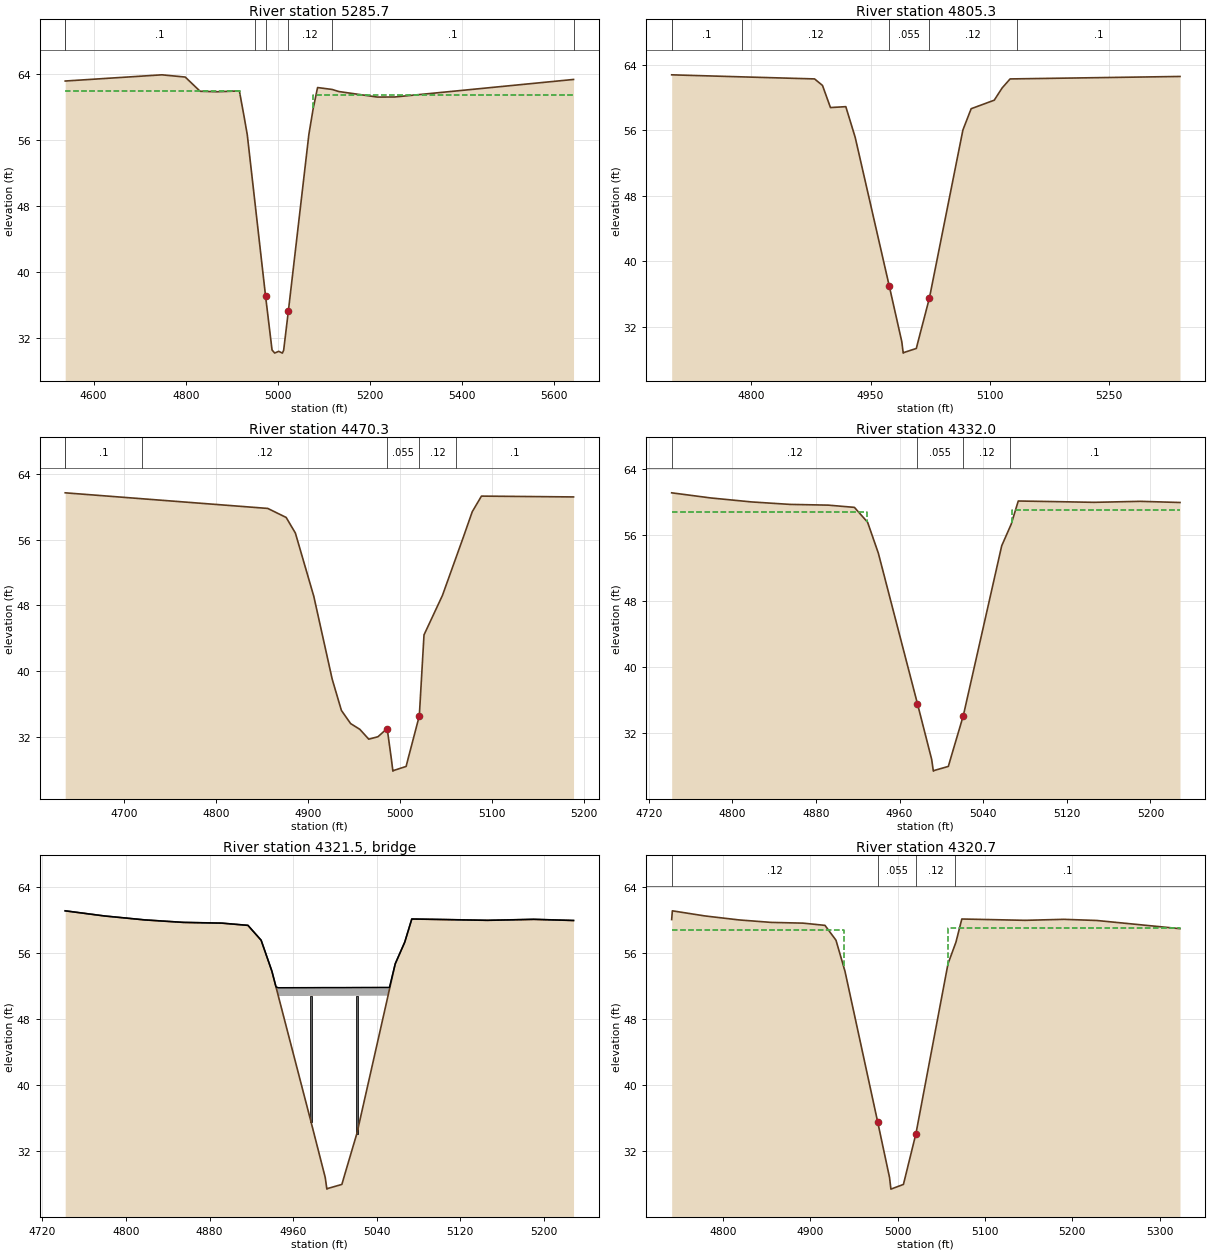
Type RM Length L Ch R = 1 ,5285.7  ,480.4,480.4,480.4
BEGIN DESCRIPTION:
Downstream Section of Bridge/Culvert/Weir
END DESCRIPTION:
XS GIS Cut Line= 6
      3083339.76     13849128.17      3083120.98     13849125.04
      3082899.36     13849123.04      3082843.09      13849120.7
      3082566.94     13849126.01      3082236.73     13849120.56
#Sta/Elev= 24
  4538.5   63.11  4748.4   63.86    4799   63.59  4831.3   61.87    4868   61.81
  4916.5   61.91  4926.8   58.79  4933.7   56.59  4950.9   48.12  4973.2   37.15
  4987.4   30.57  4993.1    30.2  5001.9   30.41  5009.8   30.19  5012.6   30.54
  5022.8   35.27  5067.4   56.68  5076.5   59.72  5086.2   62.32  5117.9   62.09
  5132.2   61.84  5215.8   61.17  5253.7   61.18  5641.7    63.3
#Mann= 7 , 1 , 0
  4538.5      .2       0  4538.5      .1       0  4950.9     .12       0
  4973.2    .055       0  5022.8     .12       0  5117.9      .1       0
  5641.7      .2       0
#XS Ineff= 2 , 0
       0    4918    61.9    5077       0    61.4
Permanent Ineff=
       F       F
Bank Sta=4973.2,5022.8
Exp/Cntr=0.5,0.3

Type RM Length L Ch R = 1 ,4805.3  ,283,335,344
BEGIN DESCRIPTION:
Cross Section 4805.3-Interpolated
END DESCRIPTION:
XS GIS Cut Line= 4
      3083193.72     13848999.97      3083010.49      13848821.7
      3082956.02     13848762.27      3082713.36     13848579.04
#Sta/Elev= 21
  4699.5    62.8    4788   62.55  4879.5    62.3  4889.5    61.5  4899.5    58.8
 4918.85   58.91 4930.65   55.17 4973.65   36.96 4989.35    30.2 4991.15   28.79
 4992.45   28.88 5007.65   29.36 5010.65    30.5 5024.15   35.52 5066.35   56.06
 5076.75   58.66  5105.8    59.7  5115.8    61.2  5125.8    62.3  5134.1   62.31
  5339.8    62.6
#Mann= 7 , 1 , 0
  4699.5      .2       0  4699.5      .1       0    4788     .12       0
 4973.65    .055       0 5024.15     .12       0  5134.1      .1       0
  5339.8      .2       0
Bank Sta=4973.65,5024.15
Exp/Cntr=0.3,0.1

Type RM Length L Ch R = 1 ,4470.3  ,127.4,138.3,146.2
BEGIN DESCRIPTION:
Cross Section 4470.3-Interpolated
END DESCRIPTION:
XS GIS Cut Line= 4
      3083294.02      13848943.3      3083207.51     13848625.14
      3083176.81     13848527.46      3083109.37     13848428.18
#Sta/Elev= 26
  4636.4    61.7  4719.7   60.98  4856.4    59.8  4876.4    58.7  4886.4    56.8
  4906.4    49.1  4926.4      39  4936.4    35.2  4946.4    33.6  4956.4    32.9
  4966.1    31.7  4976.1      32  4986.1      33 4990.73   29.22  4992.3   27.81
 4993.43    27.9 5006.66   28.38 5009.27   29.52 5021.01   34.54  5026.1    44.4
  5046.1    49.2  5060.5    53.7  5068.5    56.2  5078.5    59.4  5088.5    61.3
  5188.5    61.2
#Mann= 6 , 1 , 0
  4636.4      .2       0  4636.4      .1       0  4719.7     .12       0
  4986.1    .055       0 5021.01     .12       0  5060.5      .1       0
Bank Sta=4986.1,5021.01
Exp/Cntr=0.5,0.3

Type RM Length L Ch R = 1 ,4332.0  ,11.3,11.3,11.3
BEGIN DESCRIPTION:
Upstream Section of Bridge/Culvert/Weir
END DESCRIPTION:
XS GIS Cut Line= 4
      3083324.05     13848808.84      3083328.78     13848560.53
      3083330.39     13848517.74      3083336.81     13848322.61
#Sta/Elev= 29
 4741.91   61.09 4779.32   60.47 4818.21   59.99 4855.01   59.69 4891.73    59.6
 4916.78   59.33  4929.4   57.53 4939.67   53.79 4943.58   51.89 4945.74   50.84
 4945.93   50.74 4977.08   35.58 4990.73   28.82  4992.3   27.41 4993.43    27.5
 5006.66   27.98 5009.27   29.12 5021.01   34.14 5050.65   50.72 5050.76   50.79
 5052.16   51.57 5057.72   54.68  5065.5   56.92 5066.77   57.28 5073.56    60.1
 5107.14   60.03 5146.12   59.94  5190.4   60.06 5228.33   59.92
#Mann= 4 , 1 , 0
 4741.91     .12       0 4977.08    .055       0 5021.01     .12       0
  5065.5      .1       0
#XS Ineff= 2 , 0
       0    4929    58.8  5067.2       0      59
Permanent Ineff=
       F       F
Bank Sta=4977.08,5021.01
Exp/Cntr=0.5,0.3

Type RM Length L Ch R = 3 ,4321.5  ,,,
BEGIN DESCRIPTION:
12" DIAMETER PIPELINE, SKEW ANGLE OF 30 DEGREES
END DESCRIPTION:
Bridge Culvert--1,0,-1,-1, 0
Deck Dist Width WeirC Skew NumUp NumDn MinLoCord MaxHiCord MaxSubmerge Is_Ogee
10,1,2.6,0, 29, 29, , , 0.95, 0, 1,1,,
 4741.91 4779.32 4818.21 4855.01 4891.73 4916.78  4929.4 4939.67 4943.58 4945.74
 4945.93 4977.08 4990.73  4992.3 4993.43 5006.66 5009.27 5021.01 5050.65 5050.76
 5052.16 5057.72  5065.5 5066.77 5073.56 5107.14 5146.12  5190.4 5228.33
   61.06   60.44   59.96   59.66   59.57    59.3    57.5   53.76   51.87   51.75
   51.75   51.76   51.77   51.77   51.77   51.77   51.77   51.78   51.79   51.79
   51.79   54.65   56.89   57.25   60.07      60   59.91   60.03   59.89
   61.06   60.44   59.96   59.66   59.57    59.3    57.5   53.76   51.86   50.81
   50.75   50.76   50.77   50.77   50.77   50.77   50.77   50.78   50.79   50.76
   51.54   54.65   56.89   57.25   60.07      60   59.91   60.03   59.89
 4741.91 4779.32 4818.21 4855.01 4891.73 4916.78  4929.4 4939.67 4943.58 4945.74
 4945.93 4977.08 4990.73  4992.3 4993.43 5006.66 5009.27 5021.01 5050.65 5050.76
 5052.16 5057.72  5065.5 5066.77 5073.56 5107.14 5146.12  5190.4 5228.33
   61.06   60.44   59.96   59.66   59.57    59.3    57.5   53.76   51.87   51.75
   51.75   51.76   51.77   51.77   51.77   51.77   51.77   51.78   51.79   51.79
   51.79   54.65   56.89   57.25   60.07      60   59.91   60.03   59.89
   61.06   60.44   59.96   59.66   59.57    59.3    57.5   53.76   51.86   50.81
   50.75   50.76   50.77   50.77   50.77   50.77   50.77   50.78   50.79   50.76
   51.54   54.65   56.89   57.25   60.07      60   59.91   60.03   59.89
Pier Skew, UpSta & Num, DnSta & Num=  ,4977.1, 2 ,4977.1, 2 , 0 , 0 , 0 ,,
       2       2
   34.06   51.76
       2       2
   34.06   51.76
Pier Skew, UpSta & Num, DnSta & Num=  ,5021, 2 ,5021, 2 , 0 , 0 , 0 ,,
       2       2
   32.68   51.78
       2       2
   32.68   51.78
BR Coef= 1 , 1 , 0 ,1.25, 0 ,,,0.8,0,2,0,
WSPro=,,,, 1 ,,,, 0 ,,,, 0 ,,,,-1 ,-1 ,-1 , 0 , 0 , 0 , 0 , 0
BR U #Sta/Elev= 29
 4741.91   61.06 4779.32   60.44 4818.21   59.96 4855.01   59.66 4891.73   59.57
 4916.78    59.3  4929.4    57.5 4939.67   53.76 4943.58   51.86 4945.74   50.81
 4945.93   50.71 4977.08   35.55 4990.73   28.79  4992.3   27.38 4993.43   27.47
 5006.66   27.95 5009.27   29.09 5021.01   34.11 5050.65   50.69 5050.76   50.76
 5052.16   51.54 5057.72   54.65  5065.5   56.89 5066.77   57.25 5073.56   60.07
 5107.14      60 5146.12   59.91  5190.4   60.03 5228.33   59.89
BR U #Mann= 4
 4741.91     .12 4977.08    .055 5021.01     .12  5065.5      .1
BR U Banks=4977.08,5021.01
BR D #Sta/Elev= 29
 4741.91   61.06 4779.32   60.44 4818.21   59.96 4855.01   59.66 4891.73   59.57
 4916.78    59.3  4929.4    57.5 4939.67   53.76 4943.58   51.86 4945.74   50.81
 4945.93   50.71 4977.08   35.55 4990.73   28.79  4992.3   27.38 4993.43   27.47
 5006.66   27.95 5009.27   29.09 5021.01   34.11 5050.65   50.69 5050.76   50.76
 5052.16   51.54 5057.72   54.65  5065.5   56.89 5066.77   57.25 5073.56   60.07
 5107.14      60 5146.12   59.91  5190.4   60.03 5228.33   59.89
BR D #Mann= 4
 4741.91     .12 4977.08    .055 5021.01     .12  5065.5      .1
BR D Banks=4977.08,5021.01
BC Design=,, 0 ,, 0 ,,,,,,
BC HTab HWMax=61.09

Type RM Length L Ch R = 1 ,4320.7  ,95,95,95
BEGIN DESCRIPTION:
Upstream Section of Bridge/Culvert/Weir
END DESCRIPTION:
XS GIS Cut Line= 4
      3083333.51     13848809.06       3083341.3     13848573.12
      3083345.02     13848416.83      3083350.95     13848226.95
#Sta/Elev= 22
 4741.09      60 4741.87   61.06 4779.28   60.44 4818.17   59.96 4854.97   59.66
 4891.68   59.57 4916.74    59.3 4929.36    57.5 4939.62   53.76 4977.03   35.55
 4990.69   28.79 4992.26   27.38 5006.61   27.95 5020.97   34.11 5057.68   54.65
  5065.5    56.9 5066.73   57.25 5073.51   60.07 5146.07   59.91 5190.36   60.03
 5228.29   59.89 5323.47    58.9
#Mann= 4 , 1 , 0
 4741.09     .12       0 4977.03    .055       0 5020.97     .12       0
  5065.5      .1       0
#XS Ineff= 2 , 0
       0    4939    58.8  5057.2       0      59
Permanent Ineff=
       F       F
Bank Sta=4977.03,5020.97
Exp/Cntr=0.5,0.3

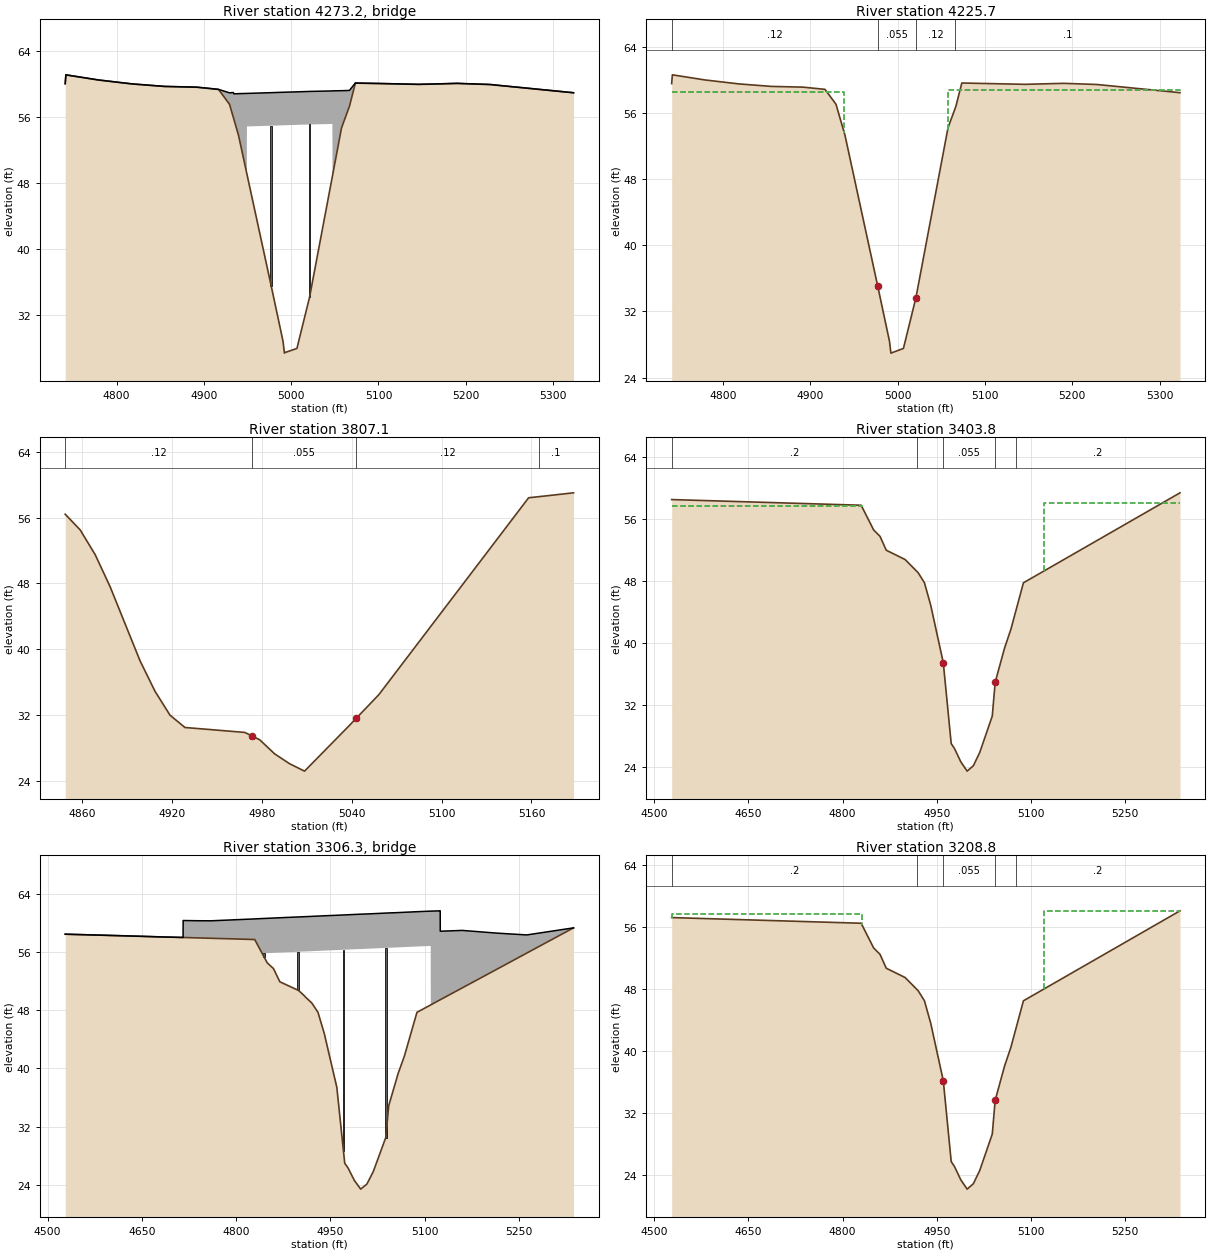
Type RM Length L Ch R = 3 ,4273.2  ,,,
BEGIN DESCRIPTION:
WIRT ROAD, SKEW ANGLE OF 30 DEGREES
Structure ID: W40-8
END DESCRIPTION:
Bridge Culvert--1,0,-1,-1, 0
Deck Dist Width WeirC Skew NumUp NumDn MinLoCord MaxHiCord MaxSubmerge Is_Ogee
10,75,2.6,0, 48, 48, , , 0.95, 0, 1,1,,
 4741.09 4741.87 4779.28 4803.38 4818.17 4854.97 4891.08 4891.68 4900.18 4900.29
 4900.39 4916.74 4929.36 4933.79 4934.14 4939.62 4949.19 4949.28 4949.54 4977.03
 4990.69 4992.26 4993.39 5006.61 5009.22 5018.62 5020.97 5046.72 5047.22 5047.33
 5057.68 5064.21  5065.5 5066.73 5073.51 5081.17 5097.93 5098.04 5098.14  5107.1
 5120.41 5146.07 5158.51 5190.36 5197.49 5228.29 5234.55 5323.47
      60   61.07   60.45   60.15   59.97   59.67   59.58   59.58   59.49   59.49
   59.49   59.31   58.89   58.93   58.77   58.79   58.82   58.82   58.82   58.91
   58.96   58.96   58.97   59.01   59.02   59.05   59.06   59.12   59.13   59.13
   59.15   59.17   59.18   59.18   60.08   60.06   60.03   60.03   60.03   60.01
   59.98   59.92   59.95   60.04   60.01    59.9   59.83    58.9
      60   61.06   60.44   60.14   59.96   59.66   59.57   59.57   59.48   59.48
   59.48    59.3    57.5   55.89   55.76   53.76    49.1   54.82   54.82   54.91
   54.96   54.96   54.97   55.01   55.02   55.05   55.06   55.12   55.13   48.86
   54.65   56.53    56.9   57.25   60.07   60.05   60.02   60.02   60.02      60
   59.97   59.91   59.94   60.03      60   59.89   59.82    58.9
 4741.09 4741.87 4779.28 4803.38 4818.17 4854.97 4891.08 4891.68 4900.18 4900.29
 4900.39 4916.74 4929.36 4933.79 4934.14 4939.62 4949.19 4949.28 4949.54 4977.03
 4990.69 4992.26 4993.39 5006.61 5009.22 5018.62 5020.97 5046.72 5047.22 5047.33
 5057.68 5064.21  5065.5 5066.73 5073.51 5081.17 5097.93 5098.04 5098.14  5107.1
 5120.41 5146.07 5158.51 5190.36 5197.49 5228.29 5234.55 5323.47
      60   61.07   60.45   60.15   59.97   59.67   59.58   59.58   59.49   59.49
   59.49   59.31   58.89   58.93   58.77   58.79   58.82   58.82   58.82   58.91
   58.96   58.96   58.97   59.01   59.02   59.05   59.06   59.12   59.13   59.13
   59.15   59.17   59.18   59.18   60.08   60.06   60.03   60.03   60.03   60.01
   59.98   59.92   59.95   60.04   60.01    59.9   59.83    58.9
   59.62   60.68   60.06   59.76   59.58   59.28   59.19   59.19    59.1    59.1
    59.1   58.92   57.12   55.51   55.38   53.38   48.72   54.44   54.44   54.53
   54.58   54.58   54.59   54.63   54.64   54.67   54.68   54.74   54.75   48.48
   54.27   56.15   56.52   56.87   59.69   59.67   59.64   59.64   59.64   59.62
   59.59   59.53   59.56   59.65   59.62   59.51   59.44   58.52
Pier Skew, UpSta & Num, DnSta & Num=  ,4977, 2 ,4977, 2 , 0 , 0 , 0 ,,
       2       2
   34.05   55.91
       2       2
   33.67   55.53
Pier Skew, UpSta & Num, DnSta & Num=  ,5021, 2 ,5021, 2 , 0 , 0 , 0 ,,
       2       2
   32.68   56.06
       2       2
    32.3   55.68
BR Coef= 1 , 1 , 0 ,1.25, 0 ,,,0.8,0,2,0,
WSPro=,,,, 1 ,,,, 0 ,,,, 0 ,,,,-1 ,-1 ,-1 , 0 , 0 , 0 , 0 , 0
BR U #Sta/Elev= 48
 4741.09      60 4741.87   61.06 4779.28   60.44 4803.38   60.14 4818.17   59.96
 4854.97   59.66 4891.08   59.57 4891.68   59.57 4900.18   59.48 4900.29   59.48
 4900.39   59.48 4916.74    59.3 4929.36    57.5 4933.79   55.89 4934.14   55.76
 4939.62   53.76 4949.19    49.1 4949.28   49.06 4949.54   48.93 4977.03   35.55
 4990.69   28.79 4992.26   27.38 4993.39   27.47 5006.61   27.95 5009.22   29.09
 5018.62   33.11 5020.97   34.11 5046.72   48.52 5047.22    48.8 5047.33   48.86
 5057.68   54.65 5064.21   56.53  5065.5    56.9 5066.73   57.25 5073.51   60.07
 5081.17   60.05 5097.93   60.02 5098.04   60.02 5098.14   60.02  5107.1      60
 5120.41   59.97 5146.07   59.91 5158.51   59.94 5190.36   60.03 5197.49      60
 5228.29   59.89 5234.55   59.82 5323.47    58.9
BR U #Mann= 4
 4741.09     .12 4977.03    .055 5020.97     .12  5065.5      .1
BR U Banks=4977.03,5020.97
BR D #Sta/Elev= 48
 4741.09   59.62 4741.87   60.68 4779.28   60.06 4803.38   59.76 4818.17   59.58
 4854.97   59.28 4891.08   59.19 4891.68   59.19 4900.18    59.1 4900.29    59.1
 4900.39    59.1 4916.74   58.92 4929.36   57.12 4933.79   55.51 4934.14   55.38
 4939.62   53.38 4949.19   48.72 4949.28   48.68 4949.54   48.55 4977.03   35.17
 4990.69   28.41 4992.26      27 4993.39   27.09 5006.61   27.57 5009.22   28.71
 5018.62   32.73 5020.97   33.73 5046.72   48.14 5047.22   48.42 5047.33   48.48
 5057.68   54.27 5064.21   56.15  5065.5   56.52 5066.73   56.87 5073.51   59.69
 5081.17   59.67 5097.93   59.64 5098.04   59.64 5098.14   59.64  5107.1   59.62
 5120.41   59.59 5146.07   59.53 5158.51   59.56 5190.36   59.65 5197.49   59.62
 5228.29   59.51 5234.55   59.44 5323.47   58.52
BR D #Mann= 4
 4741.09     .12 4977.03    .055 5020.97     .12  5065.5      .1
BR D Banks=4977.03,5020.97
BC Design=,, 0 ,, 0 ,,,,,,
BC HTab HWMax=61.06

Type RM Length L Ch R = 1 ,4225.7  ,418.6,418.6,418.6
BEGIN DESCRIPTION:
Downstream Section of Bridge/Culvert/Weir
END DESCRIPTION:
XS GIS Cut Line= 4
      3083428.12     13848800.46       3083435.9     13848564.52
      3083439.62     13848408.23      3083445.56     13848218.35
#Sta/Elev= 22
 4741.09   59.58 4741.87   60.64 4779.28   60.02 4818.17   59.54 4854.97   59.24
 4891.68   59.15 4916.74   58.88 4929.36   57.08 4939.62   53.34 4977.03   35.13
 4990.69   28.37 4992.26   26.96 5006.61   27.53 5020.97   33.69 5057.68   54.23
  5065.5   56.48 5066.73   56.83 5073.51   59.65 5146.07   59.49 5190.36   59.61
 5228.29   59.47 5323.47   58.48
#Mann= 4 , 1 , 0
 4741.09     .12       0 4977.03    .055       0 5020.97     .12       0
  5065.5      .1       0
#XS Ineff= 2 , 0
       0    4939    58.6  5057.2       0    58.8
Permanent Ineff=
       F       F
Bank Sta=4977.03,5020.97
Exp/Cntr=0.5,0.3

Type RM Length L Ch R = 1 ,3807.1  ,400.1,403.3,462.5
BEGIN DESCRIPTION:
Cross Section 3807.1-Interpolated
END DESCRIPTION:
XS GIS Cut Line= 4
      3083749.27     13848201.12       3083629.5     13848192.78
      3083570.08     13848187.83       3083411.1     13848170.57
#Sta/Elev= 20
  4848.5    56.4  4858.5    54.5  4868.5    51.5  4878.5    47.6  4898.5    38.6
  4908.5    34.9  4918.5      32  4928.5    30.5  4968.5    29.9    4973    29.5
  4978.5      29  4988.4    27.3  4998.4    26.1  5008.4    25.2  5038.1    30.7
    5043   31.63  5058.1    34.5  5158.1    58.4  5164.8   58.53  5188.1      59
#Mann= 4 , 1 , 0
  4848.5     .12       0    4973    .055       0    5043     .12       0
  5164.8      .1       0
Bank Sta=4973,5043
Exp/Cntr=0.5,0.3

Type RM Length L Ch R = 1 ,3403.8  ,195,195,195
BEGIN DESCRIPTION:
Upstream Section of Bridge/Culvert/Weir
END DESCRIPTION:
XS GIS Cut Line= 2
      3083889.84     13847827.85      3083080.44     13847827.85
#Sta/Elev= 22
  4527.9   58.48  4829.6   57.75  4849.6   54.55  4859.6   53.75  4869.6   51.95
  4899.6   50.75  4920.4   49.05  4930.4   47.75  4940.4   44.85  4960.4   37.45
    4973   27.02  4978.3   26.37  4988.3   24.67  4998.4   23.47  5008.3   24.17
  5018.4   25.87  5038.4   30.57    5043   34.92    5058   39.35    5068   41.75
    5088   47.75  5337.3   59.35
#Mann= 5 , 1 , 0
  4527.9      .2       0  4918.4     .12       0  4960.4    .055       0
    5043     .12       0  5075.5      .2       0
#XS Ineff= 2 , 0
       0    4831    57.7  5120.1       0      58
Permanent Ineff=
       F       F
Bank Sta=4960.4,5043
Exp/Cntr=0.5,0.3

Type RM Length L Ch R = 3 ,3306.3  ,,,
BEGIN DESCRIPTION:
CHIMNEY ROCK ROAD
Structure ID: W40-6
END DESCRIPTION:
Bridge Culvert--1,0,-1,-1, 0
Deck Dist Width WeirC Skew NumUp NumDn MinLoCord MaxHiCord MaxSubmerge Is_Ogee
10,175,2.6,0, 45, 45, , , 0.95, 0, 1,1,,
  4527.9  4583.4  4640.8  4687.8 4715.59  4715.7 4715.81  4738.5    4760  4829.6
 4841.11  4841.2  4841.8  4849.6  4859.6  4869.6  4899.6  4909.6  4910.4  4920.4
  4930.4  4940.4  4960.4    4973  4978.3  4988.3  4998.4  5008.3  5018.4  5038.4
    5043  5052.9    5058    5068    5088 5109.89    5110  5110.1 5124.89    5125
 5125.11    5160  5216.6  5262.9  5337.3
   58.43    58.3   58.16   58.04   57.98   60.31   60.31   60.28   60.27   60.53
   60.58   60.58   60.58   60.61   60.65   60.69    60.8   60.84   60.84   60.88
   60.92   60.96   61.03   61.08    61.1   61.14   61.18   61.21   61.25   61.33
   61.35   61.38    61.4   61.44   61.52    61.6    61.6    61.6   61.64   61.64
   58.84   58.95   58.57   58.33    59.3
   58.43    58.3   58.16   58.04   57.98   57.98   57.98   57.92   57.87    57.7
   55.86   55.84    55.8   55.83   55.87   55.91   56.02   56.06   56.06    56.1
   56.14   56.18   56.25    56.3   56.32   56.36    56.4   56.43   56.47   56.55
   56.57    56.6   56.62   56.66   56.74   56.82   48.72   48.73   49.42   49.42
   49.43   51.05   53.68   55.84    59.3
  4527.9  4583.4  4640.8  4687.8 4715.59  4715.7 4715.81  4738.5    4760  4829.6
 4841.11  4841.2  4841.8  4849.6  4859.6  4869.6  4899.6  4909.6  4910.4  4920.4
  4930.4  4940.4  4960.4    4973  4978.3  4988.3  4998.4  5008.3  5018.4  5038.4
    5043  5052.9    5058    5068    5088 5109.89    5110  5110.1 5124.89    5125
 5125.11    5160  5216.6  5262.9  5337.3
   57.73   57.86   57.71   57.56   57.51   60.31   60.31   60.28   60.27   60.53
   60.58   60.58   60.58   60.61   60.65   60.69    60.8   60.84   60.84   60.88
   60.92   60.96   61.03   61.08    61.1   61.14   61.18   61.21   61.25   61.33
   61.35   61.38    61.4   61.44   61.52    61.6    61.6    61.6   61.64   61.64
   58.84   58.95   58.57   58.33    58.6
    57.2   57.07   56.93   56.81   56.75   56.75   56.75   56.69   56.64   56.47
   54.63   54.61   54.57    54.6   54.64   54.68   54.79   54.83   54.83   54.87
   54.91   54.95   55.02   55.07   55.09   55.13   55.17    55.2   55.24   55.32
   55.34   55.37   55.39   55.43   55.51   55.59   47.49    47.5   48.19   48.19
    48.2   49.82   52.45   54.61   58.07
Pier Skew, UpSta & Num, DnSta & Num=  ,4844.8, 2 ,4844.8, 2 , 0 , 0 , 0 ,,
       3       3
   54.03   56.82
       3       3
    52.8   55.59
Pier Skew, UpSta & Num, DnSta & Num=  ,4898.3, 2 ,4898.3, 2 , 0 , 0 , 0 ,,
       3       3
   49.68   57.02
       3       3
   48.45   55.79
Pier Skew, UpSta & Num, DnSta & Num=  ,4971, 2 ,4971, 2 , 0 , 0 , 0 ,,
       3       3
   26.38    57.3
       3       3
   25.15   56.07
Pier Skew, UpSta & Num, DnSta & Num=  ,5038, 2 ,5038, 2 , 0 , 0 , 0 ,,
       3       3
   29.07   57.55
       3       3
   27.84   56.32
Abutment Skew #Up #Dn= , 2 , 2
  5052.9 5110.09
   37.79   56.82
  5052.9 5110.09
   36.56   55.59
BR Coef= 1 , 1 , 0 ,1.25, 0 ,,,0.8,0,2,0,
WSPro=,,,, 1 ,,,, 0 ,,,, 0 ,,,,-1 ,-1 ,-1 , 0 , 0 , 0 , 0 , 0
BR U #Sta/Elev= 45
  4527.9   58.43  4583.4    58.3  4640.8   58.16  4687.8   58.04 4715.59   57.98
  4715.7   57.98 4715.81   57.98  4738.5   57.92    4760   57.87  4829.6    57.7
 4841.11   55.86  4841.2   55.84  4841.8   55.75  4849.6    54.5  4859.6    53.7
  4869.6    51.9  4899.6    50.7  4909.6    49.9  4910.4    49.8  4920.4      49
  4930.4    47.7  4940.4    44.8  4960.4    37.4    4973   26.97  4978.3   26.32
  4988.3   24.62  4998.4   23.42  5008.3   24.12  5018.4   25.82  5038.4   30.52
    5043   34.87  5052.9   37.79    5058    39.3    5068    41.7    5088    47.7
 5109.89   48.72    5110   48.72  5110.1   48.73 5124.89   49.42    5125   49.42
 5125.11   49.43    5160   51.05  5216.6   53.68  5262.9   55.84  5337.3    59.3
BR U #Mann= 5
  4527.9      .2  4918.4     .12  4960.4    .055    5043     .12  5075.5      .2
BR U Banks=4960.4,5043
BR D #Sta/Elev= 45
  4527.9    57.2  4583.4   57.07  4640.8   56.93  4687.8   56.81 4715.59   56.75
  4715.7   56.75 4715.81   56.75  4738.5   56.69    4760   56.64  4829.6   56.47
 4841.11   54.63  4841.2   54.61  4841.8   54.52  4849.6   53.27  4859.6   52.47
  4869.6   50.67  4899.6   49.47  4909.6   48.67  4910.4   48.57  4920.4   47.77
  4930.4   46.47  4940.4   43.57  4960.4   36.17    4973   25.74  4978.3   25.09
  4988.3   23.39  4998.4   22.19  5008.3   22.89  5018.4   24.59  5038.4   29.29
    5043   33.64  5052.9   36.56    5058   38.07    5068   40.47    5088   46.47
 5109.89   47.49    5110   47.49  5110.1    47.5 5124.89   48.19    5125   48.19
 5125.11    48.2    5160   49.82  5216.6   52.45  5262.9   54.61  5337.3   58.07
BR D #Mann= 5
  4527.9      .2  4918.4     .12  4960.4    .055    5043     .12  5075.5      .2
BR D Banks=4960.4,5043
BC Design=,, 0 ,, 0 ,,,,,,
BC HTab HWMax=59.35

Type RM Length L Ch R = 1 ,3208.8  ,418.2,418.2,418.2
BEGIN DESCRIPTION:
Downstream Section of Bridge/Culvert/Weir
END DESCRIPTION:
XS GIS Cut Line= 2
      3083957.57     13847644.99      3083148.17     13847644.99
#Sta/Elev= 22
  4527.9   57.19  4829.6   56.46  4849.6   53.26  4859.6   52.46  4869.6   50.66
  4899.6   49.46  4920.4   47.76  4930.4   46.46  4940.4   43.56  4960.4   36.16
    4973   25.73  4978.3   25.08  4988.3   23.38  4998.4   22.18  5008.3   22.88
  5018.4   24.58  5038.4   29.28    5043   33.63    5058   38.06    5068   40.46
    5088   46.46  5337.3   58.06
#Mann= 5 , 1 , 0
  4527.9      .2       0  4918.4     .12       0  4960.4    .055       0
    5043     .12       0  5075.5      .2       0
#XS Ineff= 2 , 0
       0    4831    57.7  5120.1       0      58
Permanent Ineff=
       F       F
Bank Sta=4960.4,5043
Exp/Cntr=0.5,0.3