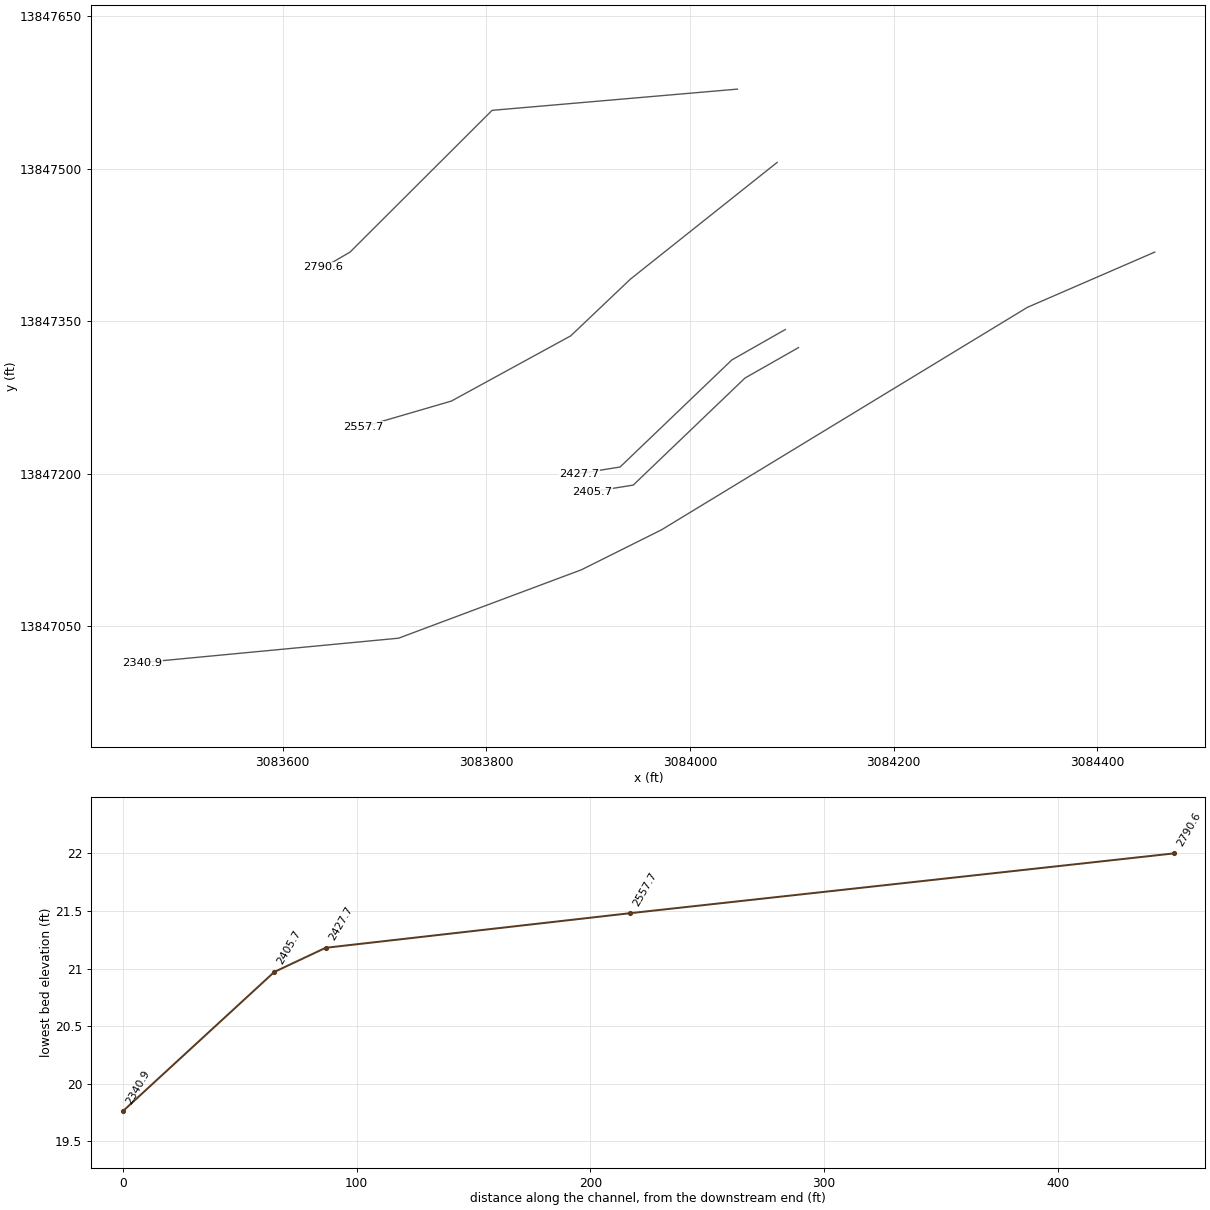
HEC-RAS study W140-00-00.PRJ: W140-00-00

--- W140-00-00.g01 (geometry) --- (continued)

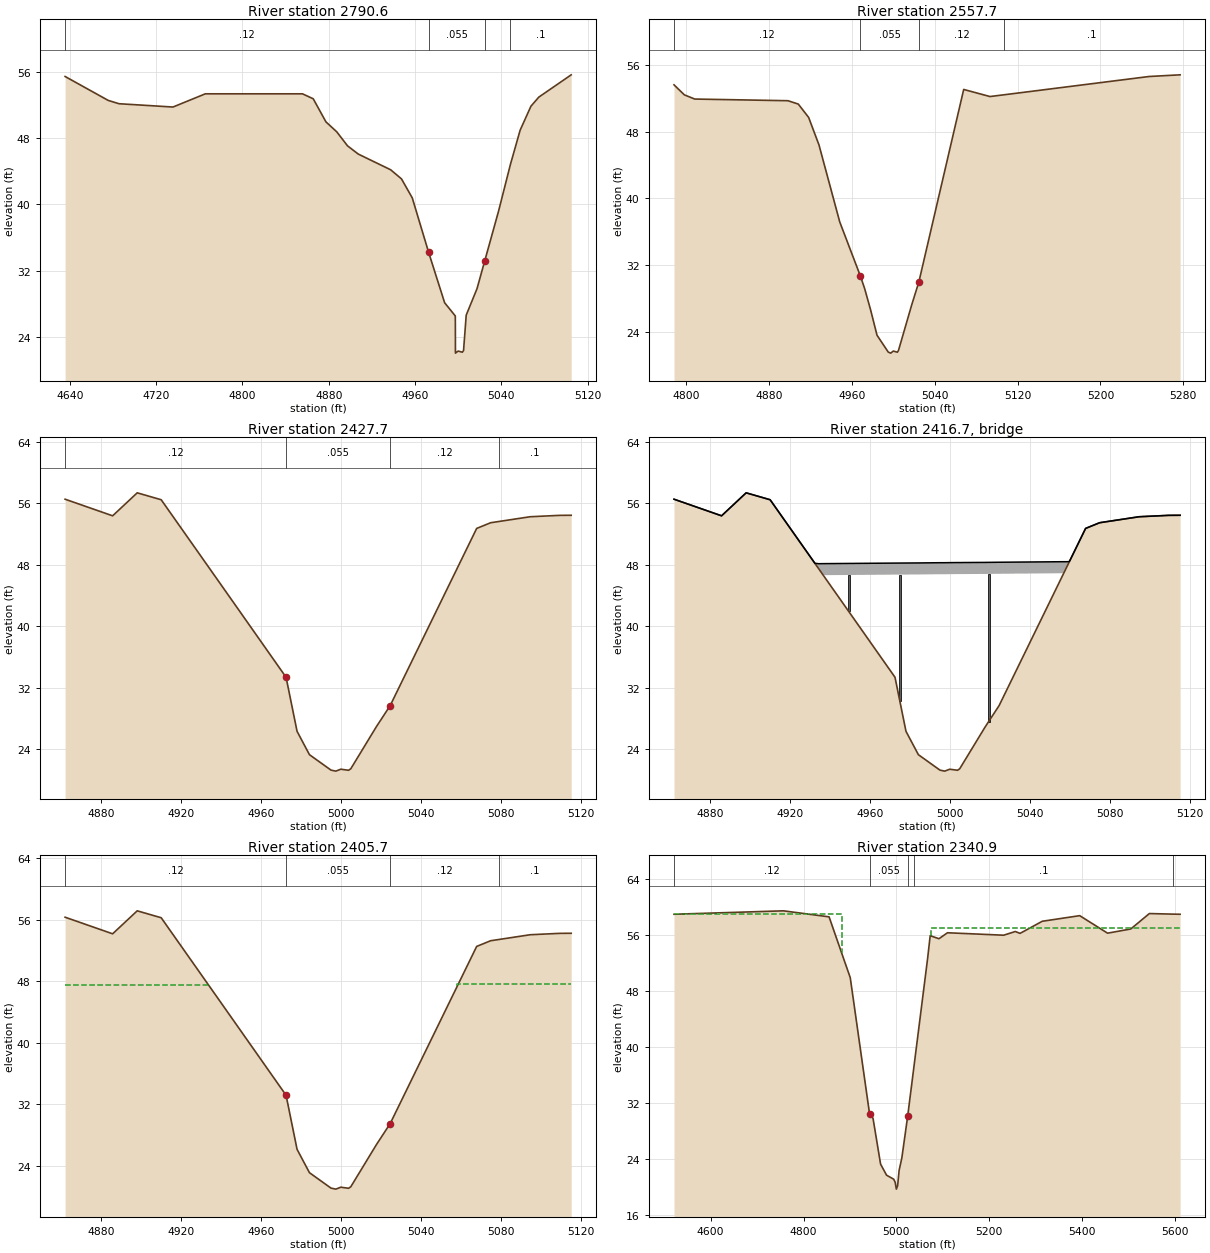
Type RM Length L Ch R = 1 ,2790.6  ,231.6,232.9,200.6
BEGIN DESCRIPTION:
Cross Section 2790.6-Interpolated
END DESCRIPTION:
XS GIS Cut Line= 4
      3084046.54     13847578.46      3083805.68     13847557.58
      3083666.13     13847418.03      3083640.21     13847402.97
#Sta/Elev= 30
  4635.6    55.5  4675.6    52.6  4685.6    52.2  4735.6    51.8  4765.6    53.4
  4855.6    53.4  4865.6    52.8  4877.4      50  4887.4    48.8  4897.4    47.1
  4907.4    46.1  4937.4    44.2  4947.4    43.1  4957.4    40.8 4972.53   34.22
  4987.4    28.1  4997.3    26.5 4997.43      22 4999.93   22.25 5003.83   22.11
 5004.93   22.31  5007.4    26.6  5017.4    29.8 5024.63    33.2  5037.4    39.2
  5048.4   44.86  5057.4      49  5067.4    51.9  5074.7      53  5104.7    55.7
#Mann= 4 , 1 , 0
  4635.6     .12       0 4972.53    .055       0 5024.63     .12       0
  5048.4      .1       0
Bank Sta=4972.53,5024.63
Exp/Cntr=0.3,0.1

Type RM Length L Ch R = 1 ,2557.7  ,89.4,130,91.8
BEGIN DESCRIPTION:
Cross Section 2557.7-Interpolated
END DESCRIPTION:
XS GIS Cut Line= 5
       3084085.5     13847506.34      3083941.52     13847391.55
      3083882.91     13847335.73      3083765.69     13847271.54
      3083679.33     13847246.29
#Sta/Elev= 24
  4788.2    53.6  4798.2    52.4  4808.2    51.9  4898.2    51.7  4908.2    51.3
  4918.2    49.7  4928.2    46.4  4948.2    37.2  4968.2    30.7  4972.3    29.2
 4978.03   26.66 4984.23   23.62 4995.03   21.61 4997.43   21.48 4999.93   21.73
 5003.83   21.59 5004.93   21.79 5017.73   27.26 5024.63      30 5067.93   53.05
  5093.3    52.2  5106.9   52.41  5246.9    54.6  5276.9    54.8
#Mann= 4 , 1 , 0
  4788.2     .12       0  4968.2    .055       0 5024.63     .12       0
  5106.9      .1       0
Bank Sta=4968.2,5024.63
Exp/Cntr=0.5,0.3

Type RM Length L Ch R = 1 ,2427.7  ,22,22,22
BEGIN DESCRIPTION:
Upstream Section of Bridge/Culvert/Weir
END DESCRIPTION:
XS GIS Cut Line= 4
      3084093.51     13847341.93      3084041.04       13847312.
      3083931.32     13847206.67      3083891.03      13847200.2
#Sta/Elev= 29
 4861.93   56.55 4885.73   54.39 4898.03   57.38 4910.03   56.48 4932.43   48.21
 4934.33   47.51 4936.84   46.58 4936.93   46.55 4952.03   40.97 4972.53   33.39
 4978.03   26.36 4984.23   23.32 4995.03   21.31 4997.43   21.18 4999.93   21.43
 5003.83   21.29 5004.93   21.49 5017.73   26.96 5024.63    29.7 5056.52   46.68
 5056.63   46.73 5058.83   47.91 5059.83   48.44 5067.93   52.75 5074.93   53.49
    5079   53.65 5094.73   54.27 5109.53   54.45 5115.23   54.46
#Mann= 4 , 1 , 0
 4861.93     .12       0 4972.53    .055       0 5024.63     .12       0
    5079      .1       0
#XS Ineff= 2 , 0
       0    4934    47.5  5058.3       0    47.6
Permanent Ineff=
       F       F
Bank Sta=4972.53,5024.63
Exp/Cntr=0.5,0.3

Type RM Length L Ch R = 3 ,2416.7  ,,,
BEGIN DESCRIPTION:
18" DIAMETER PIPELINE
END DESCRIPTION:
Bridge Culvert--1,0,-1,-1, 0
Deck Dist Width WeirC Skew NumUp NumDn MinLoCord MaxHiCord MaxSubmerge Is_Ogee
10,2,2.6,0, 29, 29, , , 0.95, 0, 1,1,,
 4861.93 4885.73 4898.03 4910.03 4932.43 4934.33 4936.84 4936.93 4952.03 4972.53
 4978.03 4984.23 4995.03 4997.43 4999.93 5003.83 5004.93 5017.73 5024.63 5056.52
 5056.63 5058.83 5059.83 5067.93 5074.93    5079 5094.73 5109.53 5115.23
   56.53   54.37   57.36   56.46    48.2   48.14   48.15   48.15   48.18   48.22
   48.23   48.24   48.27   48.27   48.28   48.29   48.29   48.31   48.33    48.4
    48.4    48.4   48.43   52.73   53.47   53.63   54.25   54.43   54.44
   56.53   54.37   57.36   56.46   48.19   47.49   46.56   46.65   46.68   46.72
   46.73   46.74   46.77   46.77   46.78   46.79   46.79   46.81   46.83    46.9
   46.71   47.89   48.42   52.73   53.47   53.63   54.25   54.43   54.44
 4861.93 4885.73 4898.03 4910.03 4932.43 4934.33 4936.84 4936.93 4952.03 4972.53
 4978.03 4984.23 4995.03 4997.43 4999.93 5003.83 5004.93 5017.73 5024.63 5056.52
 5056.63 5058.83 5059.83 5067.93 5074.93    5079 5094.73 5109.53 5115.23
   56.53   54.37   57.36   56.46    48.2   48.14   48.15   48.15   48.18   48.22
   48.23   48.24   48.27   48.27   48.28   48.29   48.29   48.31   48.33    48.4
    48.4    48.4   48.43   52.73   53.47   53.63   54.25   54.43   54.44
   56.53   54.37   57.36   56.46   48.19   47.49   46.56   46.65   46.68   46.72
   46.73   46.74   46.77   46.77   46.78   46.79   46.79   46.81   46.83    46.9
   46.71   47.89   48.42   52.73   53.47   53.63   54.25   54.43   54.44
Pier Skew, UpSta & Num, DnSta & Num=  ,4949.3, 2 ,4949.3, 2 , 0 , 0 , 0 ,,
       1       1
   40.76   47.68
       1       1
   40.76   47.68
Pier Skew, UpSta & Num, DnSta & Num=  ,4974.9, 2 ,4974.9, 2 , 0 , 0 , 0 ,,
       1       1
   28.66   47.73
       1       1
   28.66   47.73
Pier Skew, UpSta & Num, DnSta & Num=  ,5019.4, 2 ,5019.4, 2 , 0 , 0 , 0 ,,
       1       1
   26.42   47.82
       1       1
   26.42   47.82
BR Coef= 1 , 1 , 0 ,1.25, 0 ,,,0.8,0,2,0,
WSPro=,,,, 1 ,,,, 0 ,,,, 0 ,,,,-1 ,-1 ,-1 , 0 , 0 , 0 , 0 , 0
BR U #Sta/Elev= 29
 4861.93   56.53 4885.73   54.37 4898.03   57.36 4910.03   56.46 4932.43   48.19
 4934.33   47.49 4936.84   46.56 4936.93   46.53 4952.03   40.95 4972.53   33.37
 4978.03   26.34 4984.23    23.3 4995.03   21.29 4997.43   21.16 4999.93   21.41
 5003.83   21.27 5004.93   21.47 5017.73   26.94 5024.63   29.68 5056.52   46.66
 5056.63   46.71 5058.83   47.89 5059.83   48.42 5067.93   52.73 5074.93   53.47
    5079   53.63 5094.73   54.25 5109.53   54.43 5115.23   54.44
BR U #Mann= 4
 4861.93     .12 4972.53    .055 5024.63     .12    5079      .1
BR U Banks=4972.53,5024.63
BR D #Sta/Elev= 29
 4861.93   56.53 4885.73   54.37 4898.03   57.36 4910.03   56.46 4932.43   48.19
 4934.33   47.49 4936.84   46.56 4936.93   46.53 4952.03   40.95 4972.53   33.37
 4978.03   26.34 4984.23    23.3 4995.03   21.29 4997.43   21.16 4999.93   21.41
 5003.83   21.27 5004.93   21.47 5017.73   26.94 5024.63   29.68 5056.52   46.66
 5056.63   46.71 5058.83   47.89 5059.83   48.42 5067.93   52.73 5074.93   53.47
    5079   53.63 5094.73   54.25 5109.53   54.43 5115.23   54.44
BR D #Mann= 4
 4861.93     .12 4972.53    .055 5024.63     .12    5079      .1
BR D Banks=4972.53,5024.63
BC Design=,, 0 ,, 0 ,,,,,,
BC HTab HWMax=57.38

Type RM Length L Ch R = 1 ,2405.7  ,64.8,64.8,64.8
BEGIN DESCRIPTION:
Downstream Section of Bridge/Culvert/Weir
END DESCRIPTION:
XS GIS Cut Line= 4
      3084106.46     13847324.14      3084053.98     13847294.22
      3083944.26     13847188.89      3083903.98     13847182.41
#Sta/Elev= 29
 4861.93   56.34 4885.73   54.18 4898.03   57.17 4910.03   56.27 4932.43      48
 4934.33    47.3 4936.84   46.37 4936.93   46.34 4952.03   40.76 4972.53   33.18
 4978.03   26.15 4984.23   23.11 4995.03    21.1 4997.43   20.97 4999.93   21.22
 5003.83   21.08 5004.93   21.28 5017.73   26.75 5024.63   29.49 5056.52   46.47
 5056.63   46.52 5058.83    47.7 5059.83   48.23 5067.93   52.54 5074.93   53.28
    5079   53.44 5094.73   54.06 5109.53   54.24 5115.23   54.25
#Mann= 4 , 1 , 0
 4861.93     .12       0 4972.53    .055       0 5024.63     .12       0
    5079      .1       0
#XS Ineff= 2 , 0
       0    4934    47.5  5058.3       0    47.6
Permanent Ineff=
       F       F
Bank Sta=4972.53,5024.63
Exp/Cntr=0.5,0.3

Type RM Length L Ch R = 1 ,2340.9  ,123,123,123
BEGIN DESCRIPTION:
Upstream Section of Bridge/Culvert/Weir
END DESCRIPTION:
XS GIS Cut Line= 6
      3084456.25     13847418.13      3084331.16     13847363.74
        3083972.     13847144.88      3083893.43     13847105.59
      3083713.85     13847038.25      3083461.92     13847014.25
#Sta/Elev= 30
  4521.1   58.99  4756.7   59.48    4855   58.62  4900.6   49.94  4942.3   30.45
  4949.6   29.88  4965.9   23.33  4978.8   21.75  4994.1   21.18  4997.2   20.76
  4999.9   19.76  5002.6   20.24  5005.8   22.43  5011.7   24.22  5024.3   30.19
  5038.2   37.48  5067.5   52.85  5072.7   55.93  5091.6    55.5    5110   56.35
    5231      56  5256.1   56.53  5266.2   56.26  5314.1   57.99  5394.7   58.79
  5454.7   56.29  5504.7   56.89  5544.7   59.09  5594.6   59.01  5610.9   58.99
#Mann= 5 , 1 , 0
  4521.1     .12       0  4942.3    .055       0  5024.3     .12       0
  5038.2      .1       0  5594.6      .2       0
#XS Ineff= 2 , 0
       0    4882      59  5075.2       0      57
Permanent Ineff=
       F       F
Bank Sta=4942.3,5024.3
Exp/Cntr=0.5,0.3