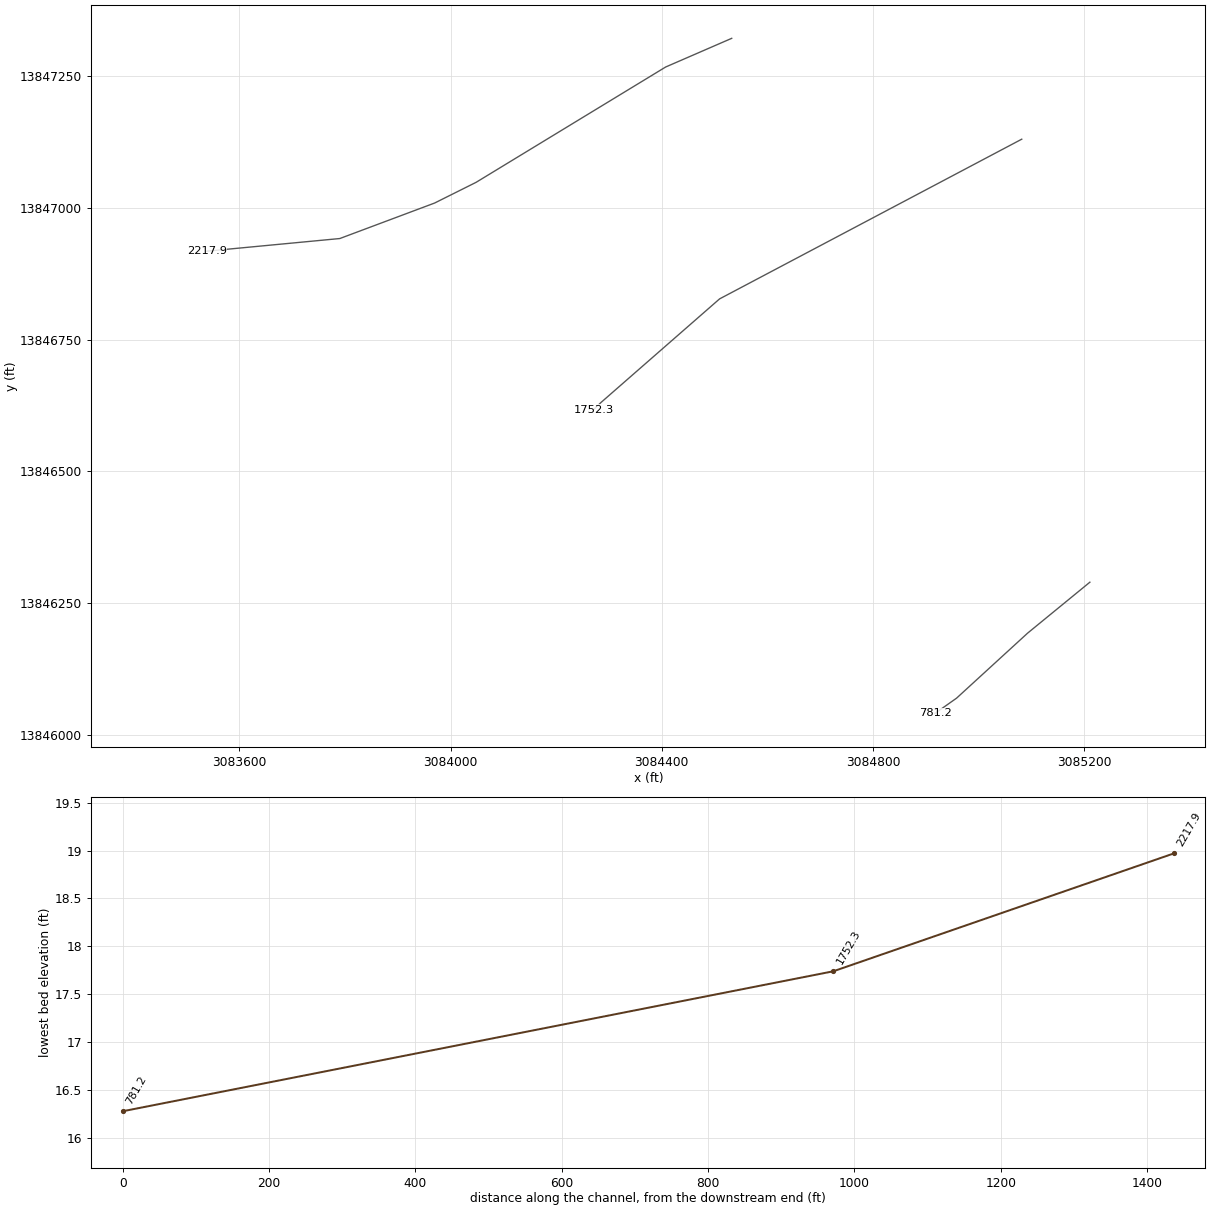
HEC-RAS study W140-00-00.PRJ: W140-00-00

--- W140-00-00.g01 (geometry) --- (continued)

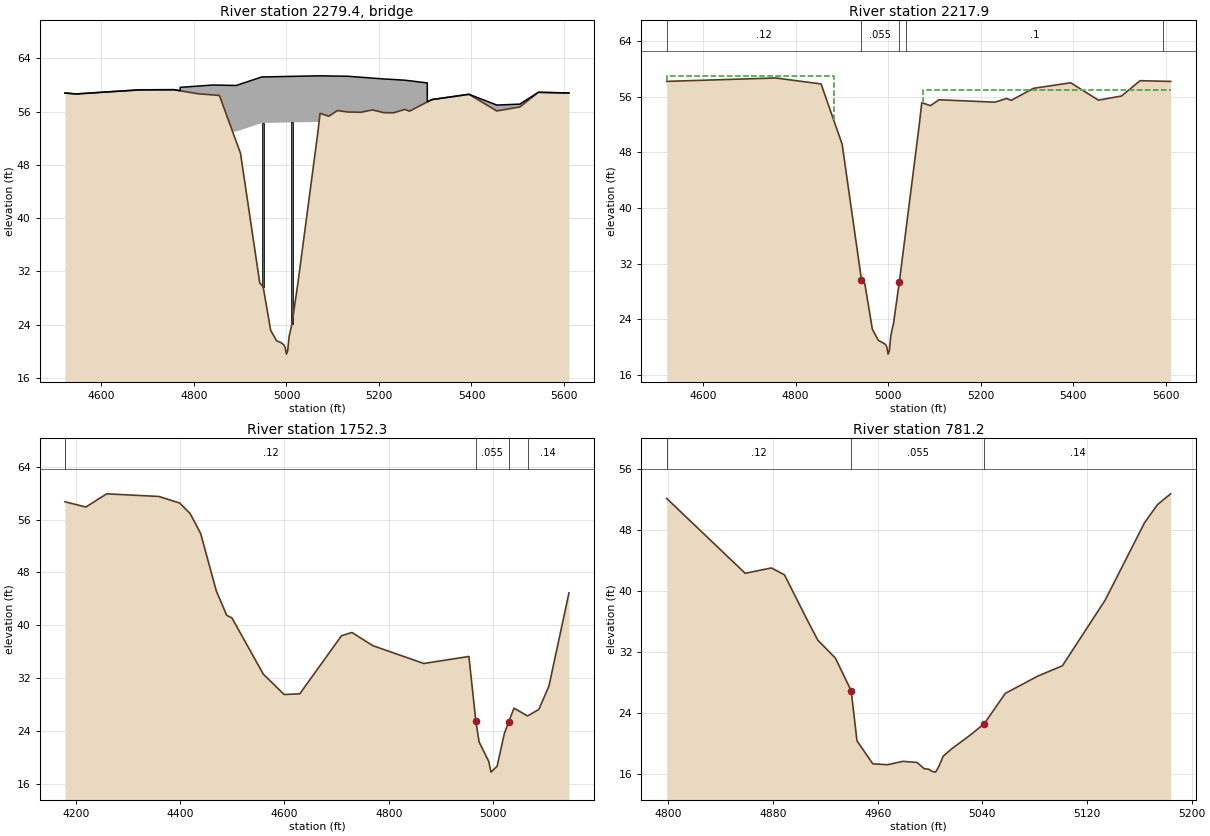
Type RM Length L Ch R = 3 ,2279.4  ,,,
BEGIN DESCRIPTION:
MEMORIAL DRIVE
Structure ID: W40-1
END DESCRIPTION:
Bridge Culvert--1,0,-1,-1, 0
Deck Dist Width WeirC Skew NumUp NumDn MinLoCord MaxHiCord MaxSubmerge Is_Ogee
10,103,2.6,0, 32, 32, , , 0.95, 0, 1,1,,
  4521.1  4545.1    4684  4756.7 4770.19  4770.3  4809.2  4840.7    4855 4884.01
  4884.1  4891.3  4946.6 5070.49  5072.7  5091.6    5110  5131.4  5160.8  5185.4
  5210.5    5231  5256.1  5266.2  5304.5 5304.61  5314.1  5394.7  5454.7  5504.7
  5544.7  5610.9
    58.8   58.66   59.28    59.3   59.14   59.65   59.84      60   59.98   59.94
   59.94   59.93   61.21   61.38   61.38   61.36   61.34   61.32   61.17   61.04
   60.91   60.83   60.72   60.64   60.31   57.47   57.81   58.61   56.99   57.13
   58.91    58.8
    58.8   58.65   59.27   59.29   59.13   59.13   58.68   58.51   58.43   52.91
   53.02   53.01   54.29   54.46   55.74   55.31   56.16   55.96    55.9   56.26
   55.85   55.81   56.34   56.07   57.45   57.46    57.8    58.6    56.1    56.7
    58.9    58.8
  4521.1  4545.1    4684  4756.7 4770.19  4770.3  4809.2  4840.7    4855 4884.01
  4884.1  4891.3  4946.6 5070.49  5072.7  5091.6    5110  5131.4  5160.8  5185.4
  5210.5    5231  5256.1  5266.2  5304.5 5304.61  5314.1  5394.7  5454.7  5504.7
  5544.7  5610.9
    58.8   58.66   59.28    59.3   59.14   59.65   59.84      60   59.98   59.94
   59.94   59.93   61.21   61.38   61.38   61.36   61.34   61.32   61.17   61.04
   60.91   60.83   60.72   60.64   60.31   57.47   57.81   58.61   56.99   57.13
   58.91    58.8
   58.23   58.08    58.7   58.72   58.56   58.56   58.11   57.94   57.86   52.34
   52.45   52.44   53.72   53.89   55.17   54.74   55.59   55.39   55.33   55.69
   55.28   55.24   55.77    55.5   56.88   56.89   57.23   58.03   55.53   56.13
   58.33   58.23
Pier Skew, UpSta & Num, DnSta & Num=  ,4949.6, 2 ,4949.6, 2 , 0 , 0 , 0 ,,
       3       3
   28.09   55.29
       3       3
   27.52   54.72
Pier Skew, UpSta & Num, DnSta & Num=  ,5011.7, 2 ,5011.7, 2 , 0 , 0 , 0 ,,
       3       3
   22.57    55.4
       3       3
      22   54.83
Abutment Skew #Up #Dn= , 2 , 2
  4883.9  4891.3
   53.02   51.52
  4883.9  4891.3
   52.45   50.95
Abutment Skew #Up #Dn= , 2 , 2
  5069.3 5070.69
   53.73   54.46
  5069.3 5070.69
   53.16   53.89
BR Coef= 1 , 1 , 0 ,1.25, 0 ,,,0.8,0,2,0,
WSPro=,,,, 1 ,,,, 0 ,,,, 0 ,,,,-1 ,-1 ,-1 , 0 , 0 , 0 , 0 , 0
BR U #Sta/Elev= 67
  4521.1    58.8  4538.9   58.69  4545.1   58.65  4580.2   58.81  4629.6   59.04
  4638.3   59.08    4684   59.27  4706.4   59.28  4756.7   59.29 4770.19   59.13
  4770.3   59.13 4770.41   59.13  4772.1   59.11  4809.2   58.68  4840.7   58.51
    4855   58.43 4884.01   52.91  4884.1   52.89  4891.2   51.54  4891.3   51.52
  4900.6   49.75  4942.3   30.26  4946.6   29.92  4949.6   29.69  4962.9   24.35
  4965.9   23.14  4978.8   21.56  4987.5   21.33  4994.1   20.99  4997.2   20.57
  4999.9   19.57  5002.6   20.05  5005.8   22.24  5011.7   24.03  5024.3      30
  5038.2   37.29  5054.7   45.95  5067.5   52.66  5069.3   53.73 5070.49   54.43
  5070.6    54.5  5072.7   55.74  5091.6   55.31    5110   56.16  5131.4   55.96
  5132.6   55.95  5160.8    55.9  5185.4   56.26  5210.5   55.85  5211.2   55.85
    5231   55.81  5256.1   56.34  5258.6   56.27  5266.2   56.07  5303.5   57.42
 5304.39   57.45  5304.5   57.45 5304.61   57.46  5314.1    57.8  5338.3   58.04
  5357.9   58.23  5394.7    58.6  5454.7    56.1  5504.7    56.7  5544.7    58.9
  5594.6   58.82  5610.9    58.8
BR U #Mann= 5
  4521.1     .12  4942.3    .055  5024.3     .12  5038.2      .1  5594.6      .2
BR U Banks=4942.3,5024.3
BR D #Sta/Elev= 67
  4521.1   58.23  4538.9   58.12  4545.1   58.08  4580.2   58.24  4629.6   58.47
  4638.3   58.51    4684    58.7  4706.4   58.71  4756.7   58.72 4770.19   58.56
  4770.3   58.56 4770.41   58.56  4772.1   58.54  4809.2   58.11  4840.7   57.94
    4855   57.86 4884.01   52.34  4884.1   52.32  4891.2   50.97  4891.3   50.95
  4900.6   49.18  4942.3   29.69  4946.6   29.35  4949.6   29.12  4962.9   23.78
  4965.9   22.57  4978.8   20.99  4987.5   20.76  4994.1   20.42  4997.2      20
  4999.9      19  5002.6   19.48  5005.8   21.67  5011.7   23.46  5024.3   29.43
  5038.2   36.72  5054.7   45.38  5067.5   52.09  5069.3   53.16 5070.49   53.86
  5070.6   53.93  5072.7   55.17  5091.6   54.74    5110   55.59  5131.4   55.39
  5132.6   55.38  5160.8   55.33  5185.4   55.69  5210.5   55.28  5211.2   55.28
    5231   55.24  5256.1   55.77  5258.6    55.7  5266.2    55.5  5303.5   56.85
 5304.39   56.88  5304.5   56.88 5304.61   56.89  5314.1   57.23  5338.3   57.47
  5357.9   57.66  5394.7   58.03  5454.7   55.53  5504.7   56.13  5544.7   58.33
  5594.6   58.25  5610.9   58.23
BR D #Mann= 5
  4521.1     .12  4942.3    .055  5024.3     .12  5038.2      .1  5594.6      .2
BR D Banks=4942.3,5024.3
BC Design=,, 0 ,, 0 ,,,,,,
BC HTab HWMax=59.48

Type RM Length L Ch R = 1 ,2217.9  ,465.6,465.6,465.6
BEGIN DESCRIPTION:
Downstream Section of Bridge/Culvert/Weir
END DESCRIPTION:
XS GIS Cut Line= 6
       3084532.6     13847321.69       3084407.5      13847267.3
      3084048.34     13847048.44      3083969.77     13847009.15
      3083790.19     13846941.81      3083538.26     13846917.81
#Sta/Elev= 30
  4521.1    58.2  4756.7   58.69    4855   57.83  4900.6   49.15  4942.3   29.66
  4949.6   29.09  4965.9   22.54  4978.8   20.96  4994.1   20.39  4997.2   19.97
  4999.9   18.97  5002.6   19.45  5005.8   21.64  5011.7   23.43  5024.3    29.4
  5038.2   36.69  5067.5   52.06  5072.7   55.14  5091.6   54.71    5110   55.56
    5231   55.21  5256.1   55.74  5266.2   55.47  5314.1    57.2  5394.7      58
  5454.7    55.5  5504.7    56.1  5544.7    58.3  5594.6   58.22  5610.9    58.2
#Mann= 5 , 1 , 0
  4521.1     .12       0  4942.3    .055       0  5024.3     .12       0
  5038.2      .1       0  5594.6      .2       0
#XS Ineff= 2 , 0
       0    4882      59  5075.2       0      57
Permanent Ineff=
       F       F
Bank Sta=4942.3,5024.3
Exp/Cntr=0.5,0.3

Type RM Length L Ch R = 1 ,1752.3  ,947,971.1,909.3
BEGIN DESCRIPTION:
Cross Section 1752.3
END DESCRIPTION:
XS GIS Cut Line= 4
      3085082.05     13847130.33      3084509.63     13846827.28
      3084285.15     13846630.87       3084270.8     13846616.91
#Sta/Elev= 30
  4179.5    58.7  4219.5    57.9  4259.5    59.9  4359.5    59.5  4399.5    58.5
  4419.5    56.9  4439.5    53.9  4469.5    45.2  4489.5    41.5  4499.5    41.1
  4559.5    32.6  4599.5    29.5  4629.5    29.6  4709.5    38.4  4729.5    38.9
  4769.5    36.9  4867.2    34.2  4953.7   35.26  4966.9   25.54  4973.2   22.32
  4991.7   19.37    4996   17.74  5007.7   18.62  5021.7   23.59  5029.7   25.29
  5040.1   27.43  5066.2   26.25  5087.8   27.24  5107.2    30.8  5145.5    44.9
#Mann= 5 , 1 , 0
  4179.5      .2       0  4179.5     .12       0  4966.9    .055       0
  5029.7     .12       0  5066.2     .14       0
Bank Sta=4966.9,5029.7
Exp/Cntr=0.3,0.1

Type RM Length L Ch R = 1 ,781.2   ,0,0,0
BEGIN DESCRIPTION:
Cross Section 781.2
END DESCRIPTION:
XS GIS Cut Line= 4
      3085211.12     13846289.71      3085093.27     13846193.14
      3084958.59     13846069.67      3084917.74     13846040.78
#Sta/Elev= 29
  4798.8    52.1  4858.8    42.3  4878.8      43  4888.8    42.1  4906.3   36.16
  4914.3   33.55  4927.7   31.21  4939.8   26.92  4944.2   20.38  4956.3   17.37
  4967.5   17.25  4979.3   17.69  4990.1   17.55  4995.6   16.73    4999   16.66
  5001.5   16.39  5004.3   16.28  5006.8   17.03  5010.1   18.37  5016.6   19.34
  5029.8      21  5041.5   22.62  5057.5   26.58  5082.3   28.84  5101.2    30.2
  5133.9    38.8  5163.9    48.9  5173.9    51.3  5183.9    52.7
#Mann= 3 , 1 , 0
  4798.8     .12       0  4939.8    .055       0  5041.5     .14       0
Bank Sta=4939.8,5041.5
Exp/Cntr=0.3,0.1

Chan Stop Cuts=-1
Use User Specified Reach Order=0
User Specified Reach Order=W140-00-00      ,Reach - 1